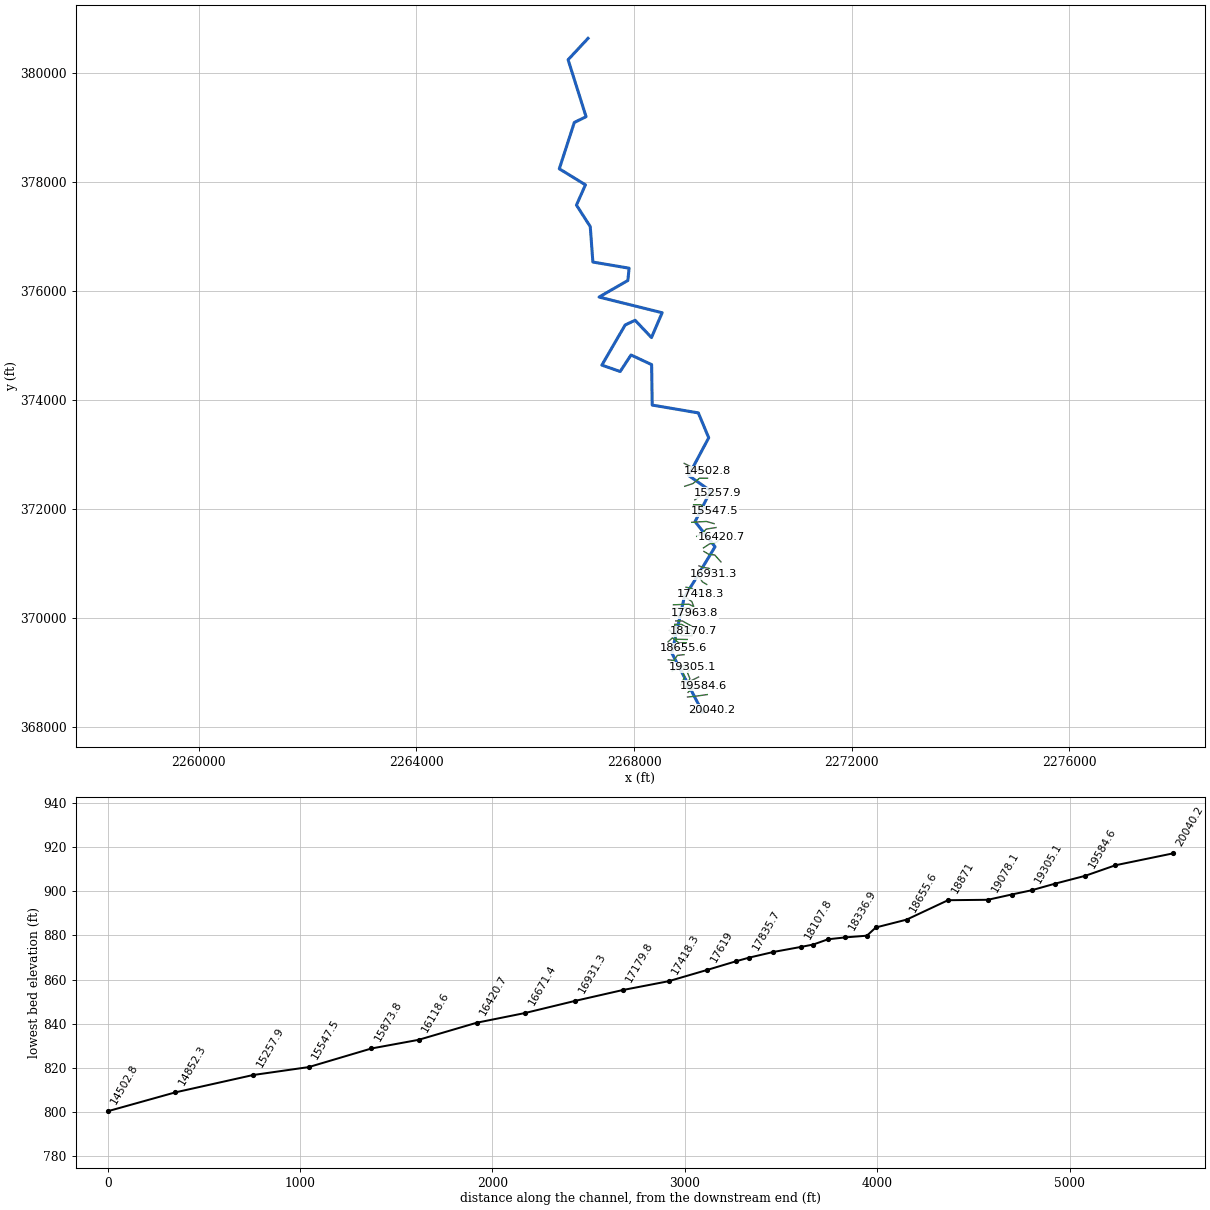
--- BIGRUN1.prj (project) ---

Proj Title=BIGRUN1
Current Plan=p01
Default Exp/Contr=0,0
English Units
Geom File=g01
Flow File=f01
Plan File=p01
BEGIN DESCRIPTION:
END DESCRIPTION:
DSS Export Rating Curves= 0
DSS Export Rating Curve Sorted= 0
DSS Export Volume Flow Curves= 0
DXF OffsetX= 0
DXF OffsetY= 0
DXF ScaleX= 0
DXF ScaleY= 0

--- BIGRUN1.p01 (plan) ---

Plan Title=Floodplain
Program Version=4.00
Geom File=g01
Flow File=f01
K Sum by GR=0
Std Step Tol=0.01
Critical Tol=0.01
Num of Std Step Trials=20
Max Error Tol=0.3
Flow Tol Ratio=0.001
Split Flow NTrial=30
Split Flow Tol=0.02
Split Flow Ratio=0.02
Log Output Level=0
Friction Slope Method=1
Unsteady Friction Slope Method=2
Unsteady Bridges Friction Slope Method=1
Global Log Level=0
CheckData=False
Run HTab=0
Run UNet=0
Run PostProcess=0
UNET Theta=0
UNET Theta Warmup=0
UNET ZTol=0
UNET ZSATol=0
UNET MxIter=0
UNET MaxInSteps=0
UNET DtIC=0
UNET DtMin=0
UNET MaxCRTS=0
UNET WFStab=0
UNET SFStab=0
UNET WFX=0
UNET SFX=0
UNET DSS MLevel=0
UNET DZMax Abort=0
UNET Convert EG Bridges=0
UNET Use Existing IB Tables=0
UNET Froude Limit=0
UNET Froude Power=0
Write IC File=0
Echo Input=False
Echo Output=False
Write Detailed=0

--- BIGRUN1.f01 (steady flow) ---

Flow Title=NFF Regression Equation
Program Version=4.00
Number of Profiles=1
Profile Names=P100yr
River Rch & RM=BIGRUN1,Main      ,20040.2
538.0701
River Rch & RM=BIGRUN1,Main      ,19584.6
559.1457
River Rch & RM=BIGRUN1,Main      ,18871
617.8331
River Rch & RM=BIGRUN1,Main      ,17766.7
648.8110
River Rch & RM=BIGRUN1,Main      ,17418.3
721.7795
River Rch & RM=BIGRUN1,Main      ,14004.8
798.3219
River Rch & RM=BIGRUN1,Main      ,13702.6
901.7900
River Rch & RM=BIGRUN1,Main      ,13375
1012.436
River Rch & RM=BIGRUN1,Main      ,11448.5
1115.317
River Rch & RM=BIGRUN1,Main      ,1693.1
1238.643
River Rch & RM=BIGRUN1,Main      ,1490.1
1469.350
River Rch & RM=BIGRUN1,Main      ,661.4
1472.382
River Rch & RM=BIGRUN1,Main      ,420.4
1477.937
Boundary for River Rch & Prof#=BIGRUN1,Main      ,1
Up Type=0
Dn Type=3
Dn Slope=0.036696

--- BIGRUN1.g01 (geometry) ---

Geom Title=USGS 10m DEM
Program Version=5.03

River Reach=BIGRUN1         ,Main
Reach XY= 30
     2269256.491      368270.777     2268693.883      369352.059
      2268920.13      370367.303     2269487.969      371305.584
     2269120.651      371766.912     2269405.932      372329.916
     2269002.143      372614.193     2269371.595      373306.742
     2269181.073      373763.549      2268332.64      373907.514
      2268322.48       374650.57     2267943.573      374827.351
     2267744.206      374523.864     2267407.314       374641.46
     2267835.761       375378.44     2268018.933      375465.329
     2268319.229      375147.477     2268515.927      375603.272
     2267356.351      375891.592     2267885.337      376196.055
     2267908.358      376421.621     2267242.372        376534.6
     2267194.502      377185.342     2266940.379      377581.036
     2267105.957      377952.859     2266625.353      378247.492
     2266901.196      379098.412     2267117.461      379204.312
      2266786.97      380250.846     2267153.607      380643.774

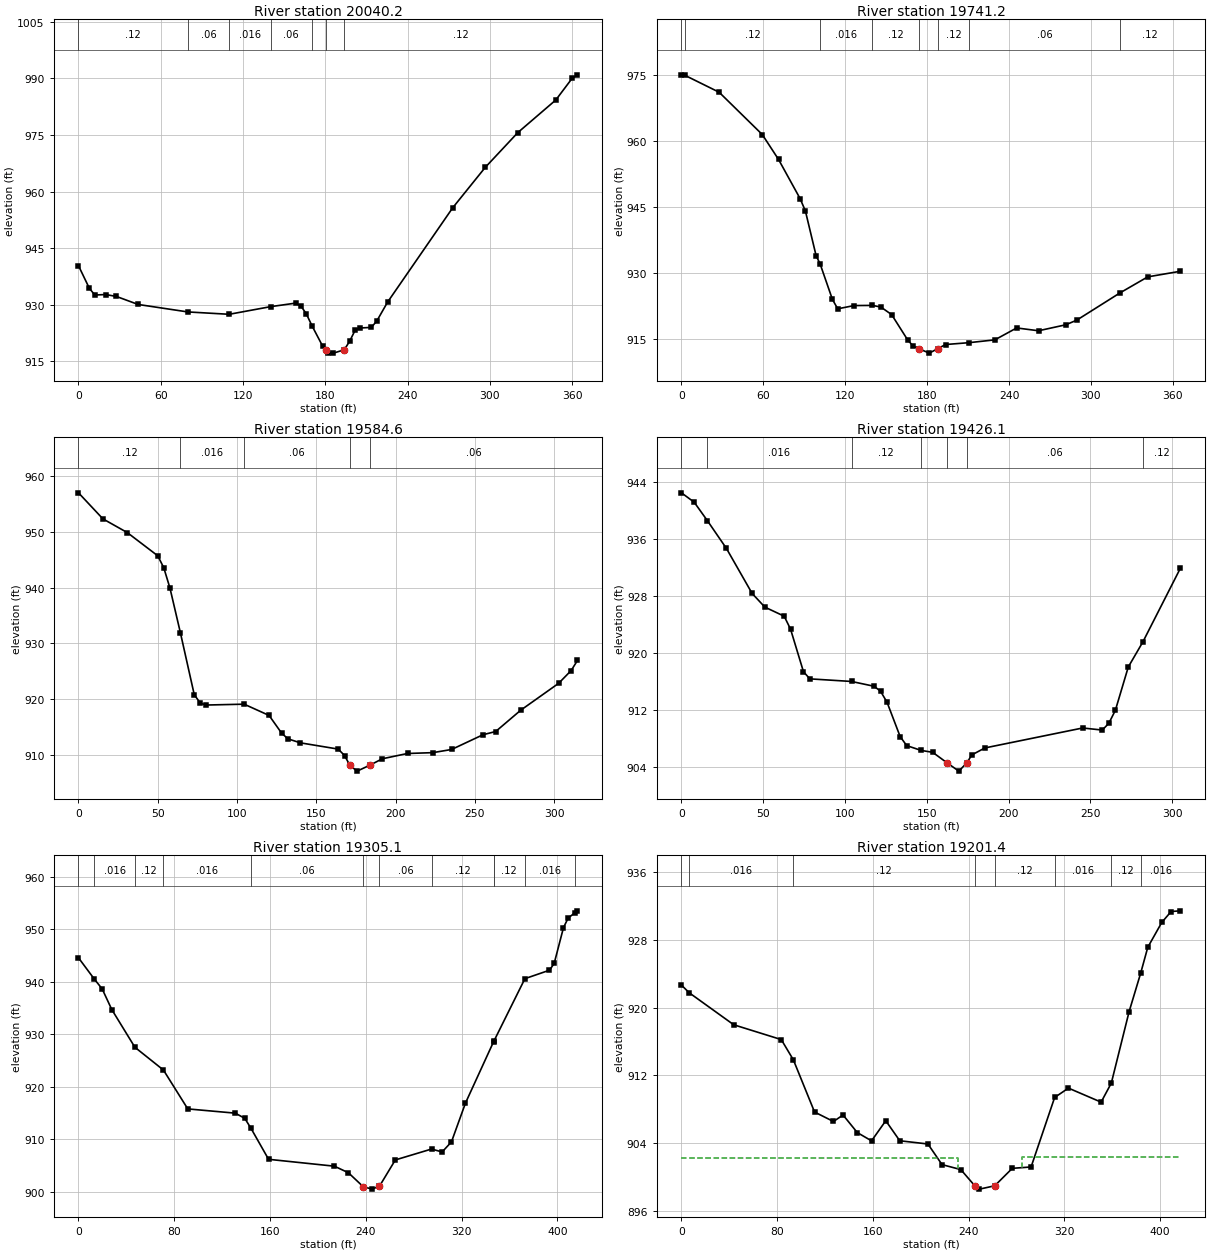
Type RM Length L Ch R = 1 ,20040.2 ,300.7,298.9,297.4
XS GIS Cut Line= 3
     2269073.939      368244.466     2269252.439      368279.985
      2269430.94      368315.504
#Sta/Elev= 30
       0  940.33     7.9  934.36    11.9  932.56    19.8  932.69    27.7  932.18
    43.5  930.06   79.74928.0788  109.94927.4543  140.14929.4788   158.3  930.41
   162.2  929.68   166.2  927.56  170.34924.4008     178  919.08  180.48917.9826
     182  917.31     186  917.16   193.9  918.06   197.8  920.32   201.8  923.23
   205.7  923.83   213.6  923.98   217.6  925.68   225.5   930.7     273   955.7
   296.7  966.39   320.5  975.63   348.2  984.27     360  989.96     364  990.93
#Mann= 7 ,-1 , 0
       0     .12       0   79.74     .06       0  109.94    .016       0
  140.14     .06       0  170.34     .12       0  180.48    .045       0
   193.9     .12       0
Bank Sta=180.48,193.9
XS Rating Curve= 0 ,0
Exp/Cntr=0.3,0.1

Type RM Length L Ch R = 1 ,19741.2 ,152.3,156.6,159.4
XS GIS Cut Line= 3
     2268982.175      368544.999     2269162.809      368563.926
     2269344.934      368590.068
#Sta/Elev= 30
       0  975.11    2.59974.9869    27.6  971.15    59.2  961.53    71.1  955.87
    86.9  946.96    90.8  944.14    98.7   933.9  101.51932.1578   110.6  924.01
   114.5  921.87   126.4  922.61  139.96922.6475   146.1  922.28     154  920.55
   165.8  914.76   169.8  913.38   173.7  912.83   181.6  911.79  187.86912.8292
   193.6  913.75  210.69914.1682   229.6  914.81   245.6  917.52   261.6  916.88
   281.6  918.24   289.6  919.29  321.31925.4976   341.6  929.14   365.6  930.42
#Mann= 8 ,-1 , 0
       0     .06       0    2.59     .12       0  101.51    .016       0
  139.96     .12       0   173.7    .045       0  187.86     .12       0
  210.69     .06       0  321.31     .12       0
Bank Sta=173.7,187.86
XS Rating Curve= 0 ,0
Exp/Cntr=0.3,0.1

Type RM Length L Ch R = 1 ,19584.6 ,153.9,158.4,162.2
XS GIS Cut Line= 3
     2268991.583      368630.483     2269055.385      368691.681
     2269272.833      368754.181
#Sta/Elev= 30
       0  957.04    15.4  952.36    30.8  949.89      50  945.72    53.8  943.56
    57.7   939.9   64.26931.8964      73  920.77    76.9  919.21    80.7   918.9
  104.47919.0543   120.2  917.03   128.1  913.85   132.1  912.82     140   912.1
   163.8  910.98   167.8  909.82   171.2  908.04   175.7  907.02   183.7  908.08
   191.6  909.24   207.5  910.19   223.4  910.34   235.3  910.91   255.1  913.56
   263.1  914.14   278.9  917.97   302.8   922.8   310.7   925.1   314.7  926.92
#Mann= 5 ,-1 , 0
       0     .12       0   64.26    .016       0  104.47     .06       0
   171.2    .045       0   183.7     .06       0
Bank Sta=171.2,183.7
XS Rating Curve= 0 ,0
Exp/Cntr=0.3,0.1

Type RM Length L Ch R = 1 ,19426.1 ,39.4,121,160.5
XS GIS Cut Line= 3
     2268968.145      368721.629     2269021.531      368831.004
     2269185.593      368913.035
#Sta/Elev= 30
       0  942.46     7.8  941.14   15.78938.5782    27.5  934.66    43.2  928.35
      51  926.43    62.8  925.16    66.7  923.34    74.6  917.37    78.5  916.37
  103.98916.0051   117.8  915.33   121.7  914.64   125.7  913.09   133.7  908.28
   137.7  907.01  146.57 906.333   153.6  906.07   162.4  904.59   169.6  903.43
  174.61904.6268   177.5   905.7   185.5  906.68   245.3  909.48   257.3  909.19
   261.3  910.14   265.3  911.96   273.2  918.04  282.16  921.57   305.1  931.91
#Mann= 7 ,-1 , 0
       0     .06       0   15.78    .016       0  103.98     .12       0
  146.57     .06       0   162.4    .045       0  174.61     .06       0
  282.16     .12       0
Bank Sta=162.4,174.61
XS Rating Curve= 0 ,0
Exp/Cntr=0.3,0.1

Type RM Length L Ch R = 1 ,19305.1 ,148,103.7,110.8
XS GIS Cut Line= 4
     2268954.083      368728.139     2269025.697      368883.087
     2268980.259      368995.646      2269064.76      369087.514
#Sta/Elev= 30
       0  944.52   13.13940.4955    19.8  938.59    27.8  934.67   47.13927.4807
   70.97923.1427    91.3  915.74     131  914.93   138.9  913.95  143.96 912.101
   158.8  906.14   213.8  904.83   225.5  903.58   237.7  900.96   245.1  900.46
  251.44901.0082   264.7  906.02  294.95908.0954   303.8  907.54   311.6  909.46
   323.3  916.85  346.79928.5372  346.99928.6197  372.97940.5499   393.5  942.16
   397.4  943.44   405.2  950.28   409.1  952.09  414.45953.0554   416.9  953.47
#Mann= 12 ,-1 , 0
       0     .06       0   13.13    .016       0   47.13     .12       0
   70.97    .016       0  143.96     .06       0   237.7    .045       0
  251.44     .06       0  294.95     .12       0  346.79     .06       0
  346.99     .12       0  372.97    .016       0  414.45     .06       0
Bank Sta=237.7,251.44
XS Rating Curve= 0 ,0
Exp/Cntr=0.3,0.1

Type RM Length L Ch R = 1 ,19201.4 ,161.3,123.3,75.6
XS GIS Cut Line= 4
     2268857.989      368761.212     2268929.604       368916.16
     2268884.165      369028.719     2268968.666      369120.587
#Sta/Elev= 30
       0  922.67    6.58 921.756    43.7  917.98    83.4  916.23    93.5913.8305
   111.2  907.66     127  906.54     135  907.31   146.9  905.23   158.8  904.25
   170.7  906.63   182.4  904.26   205.9  903.88   217.7  901.44   233.4  900.85
   245.1  898.93     249  898.54  261.73898.9349   276.4     901   292.1  901.16
  311.78 909.382   323.3  910.49   350.6  908.83  359.14911.0871     374  919.54
  383.69924.1019   389.6  927.15   401.3  930.09   409.1  931.38   416.9  931.46
#Mann= 8 ,-1 , 0
       0     .06       0    6.58    .016       0    93.5     .12       0
   245.1    .045       0  261.73     .12       0  311.78    .016       0
  359.14     .12       0  383.69    .016       0
#XS Ineff= 2 , 0
          230.65  902.23  284.31           902.3
Permanent Ineff=
       F       F
Bank Sta=245.1,261.73
XS Rating Curve= 0 ,0
Exp/Cntr=0.3,0.1

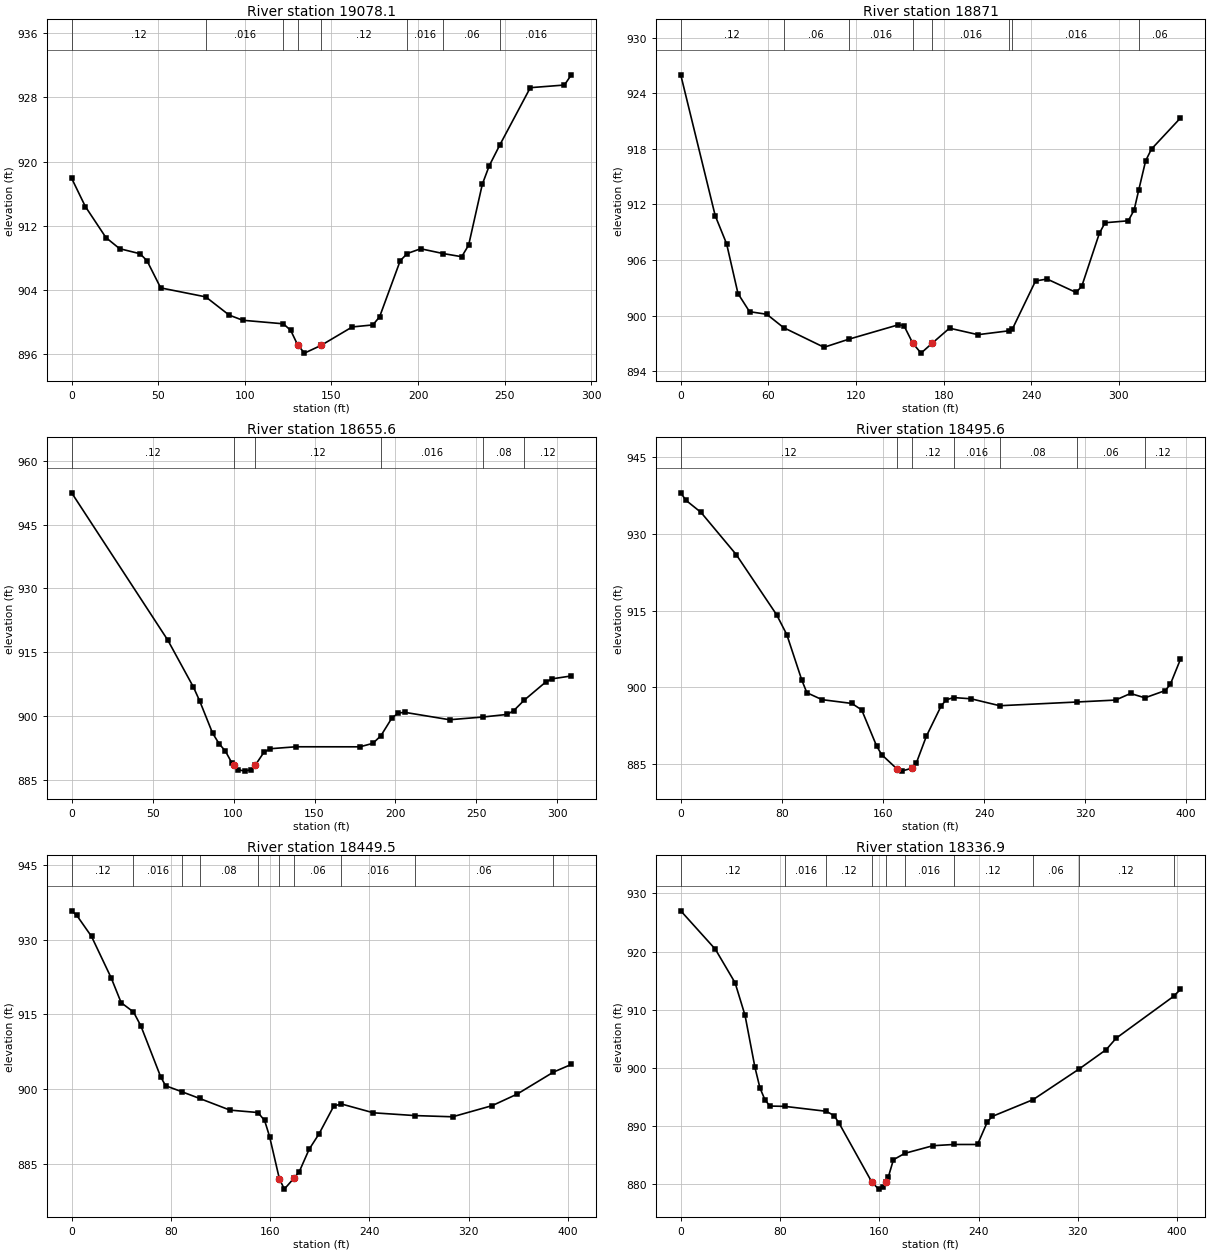
Type RM Length L Ch R = 1 ,19078.1 ,194.1,207.1,218.1
XS GIS Cut Line= 2
     2268699.916      369023.712     2268962.937      369142.202
#Sta/Elev= 30
       0  917.92     7.9  914.41    19.8  910.54    27.7  909.16    39.5  908.53
    43.5  907.66    51.4  904.28   77.42903.1611    90.9   900.9    98.8  900.25
  122.27899.8094   126.5  898.98   130.4  897.22   134.4  896.16   143.9  897.11
     162  899.42   173.9  899.67   177.8  900.68   189.7  907.66  193.75908.5565
   201.5  909.15  214.49908.5546   225.2  908.16   229.2   909.6   237.1  917.18
   241.1  919.48  247.17 922.056   264.8   929.2   284.5  929.53   288.5   930.8
#Mann= 8 ,-1 , 0
       0     .12       0   77.42    .016       0  122.27     .12       0
   130.4    .045       0   143.9     .12       0  193.75    .016       0
  214.49     .06       0  247.17    .016       0
Bank Sta=130.4,143.9
XS Rating Curve= 0 ,0
Exp/Cntr=0.3,0.1

Type RM Length L Ch R = 1 ,18871   ,236.3,215.4,192.3
XS GIS Cut Line= 4
     2268625.697      369228.139     2268731.166      369217.722
      2268796.27       369310.17     2268918.666      369323.191
#Sta/Elev= 30
       0  925.98    23.6  910.79    31.4  907.76    39.2  902.39    47.1  900.44
    58.9  900.16   70.39898.7216    98.1   896.6  114.99897.4688   148.9  899.02
   152.8  898.94  158.82897.0493   164.5  895.97   172.3  897.06     184  898.66
   203.5  897.96  224.81898.3802  227.02898.5571   242.9  903.75   250.8  903.96
   270.7  902.51   274.6   903.2   286.6  908.89   290.5  910.03   306.4  910.24
   310.4   911.4  313.51913.5304   318.3  916.72   322.3  917.98   342.1  921.32
#Mann= 8 ,-1 , 0
       0     .12       0   70.39     .06       0  114.99    .016       0
  158.82    .045       0   172.3    .016       0  224.81     .12       0
  227.02    .016       0  313.51     .06       0
Bank Sta=158.82,172.3
XS Rating Curve= 0 ,0
Exp/Cntr=0.3,0.1

Type RM Length L Ch R = 1 ,18655.6 ,174.9,160,145.2
XS GIS Cut Line= 2
     2268597.052      369444.285     2268905.645      369441.681
#Sta/Elev= 30
       0  952.43    59.4  917.87    75.2  906.88    79.1   903.6      87   896.1
      91  893.64      95  891.83    98.9  889.11  100.21 888.586   102.9  887.51
   106.8  887.17   110.8  887.53   113.4  888.57   118.7  891.56   122.6  892.42
   138.5  892.88     178  892.87     186  893.68  190.96895.4536   197.8  899.64
   201.8   900.8   205.7  900.96   233.4  899.22  254.24 899.869     269  900.47
     273  901.35  279.52903.8157   292.8  908.07   296.7  908.81   308.6  909.49
#Mann= 6 ,-1 , 0
       0     .12       0  100.21    .045       0   113.4     .12       0
  190.96    .016       0  254.24     .08       0  279.52     .12       0
Bank Sta=100.21,113.4
XS Rating Curve= 0 ,0
Exp/Cntr=0.3,0.1

Type RM Length L Ch R = 1 ,18495.6 ,51.9,46.1,33.7
XS GIS Cut Line= 4
     2268624.395      369557.566     2268703.822      369630.483
     2268826.218      369538.035     2268960.333      369541.941
#Sta/Elev= 30
       0  938.06       4  936.62      16  934.24    43.9  925.98    75.9   914.2
    83.9  910.34    95.8  901.42    99.8  898.96   111.8   897.6   135.4  896.86
   143.2  895.59     155  888.53     159  886.84   170.8  884.12   174.7  883.62
   182.6  884.17   186.5  885.26   194.4  890.47   206.2  896.44   210.1  897.56
  215.88898.0111   229.7  897.77  252.42896.4148   313.2897.1377   344.1  897.52
   355.9  898.81  367.32897.9604   383.5  899.39   387.5  900.66   395.4  905.49
#Mann= 7 ,-1 , 0
       0     .12       0   170.8    .045       0   182.6     .12       0
  215.88    .016       0  252.42     .08       0   313.2     .06       0
  367.32     .12       0
Bank Sta=170.8,182.6
XS Rating Curve= 0 ,0
Exp/Cntr=0.3,0.1

Type RM Length L Ch R = 1 ,18449.5 ,112.6,112.6,117.1
XS GIS Cut Line= 3
     2268653.041      369771.108     2268784.552      369605.743
     2268975.958      369601.837
#Sta/Elev= 30
       0  935.81       4  934.94      16  930.67    31.9  922.32    39.9  917.36
   49.84915.4925    55.8  912.69    71.8  902.44    75.7  900.68   88.86899.4669
  103.08898.1293   127.6  895.78  150.11895.2973   155.5   893.7   159.5  890.48
   167.4  881.99   171.4  879.91   179.4  882.18   183.4  883.39   191.4  887.92
   199.3  890.98   211.3  896.62  217.45897.0101   243.2  895.24  276.49894.6852
     307  894.44   338.9  896.68   358.9  898.98  388.28903.4161   402.7  904.96
#Mann= 10 ,-1 , 0
       0     .12       0   49.84    .016       0   88.86     .12       0
  103.08     .08       0  150.11     .12       0   167.4    .045       0
   179.4     .06       0  217.45    .016       0  276.49     .06       0
  388.28     .12       0
Bank Sta=167.4,179.4
XS Rating Curve= 0 ,0
Exp/Cntr=0.3,0.1

Type RM Length L Ch R = 1 ,18336.9 ,77.7,89.7,99.4
XS GIS Cut Line= 3
     2268740.281      369838.816     2268871.791      369673.452
     2269063.197      369669.545
#Sta/Elev= 30
       0     927    27.9  920.39    43.8  914.62    51.8  909.03    59.8  900.08
    63.8  896.55    67.8  894.53    71.8  893.42    83.8893.3663  117.35892.5162
   123.6  891.77   127.6  890.47     154  880.34   159.5  879.13   163.4   879.5
  165.18880.2966   167.4  881.29   171.4  884.19  180.69885.2954   203.3   886.6
  219.91886.8106   239.2  886.81   247.2  890.75   251.2  891.65  283.93894.5183
  321.06899.7947   342.9  903.13   350.9  905.09  397.17912.2883   402.7  913.48
#Mann= 10 ,-1 , 0
       0     .12       0    83.8    .016       0  117.35     .12       0
     154    .045       0  165.18     .12       0  180.69    .016       0
  219.91     .12       0  283.93     .06       0  321.06     .12       0
  397.17     .06       0
Bank Sta=154,165.18
XS Rating Curve= 0 ,0
Exp/Cntr=0.3,0.1

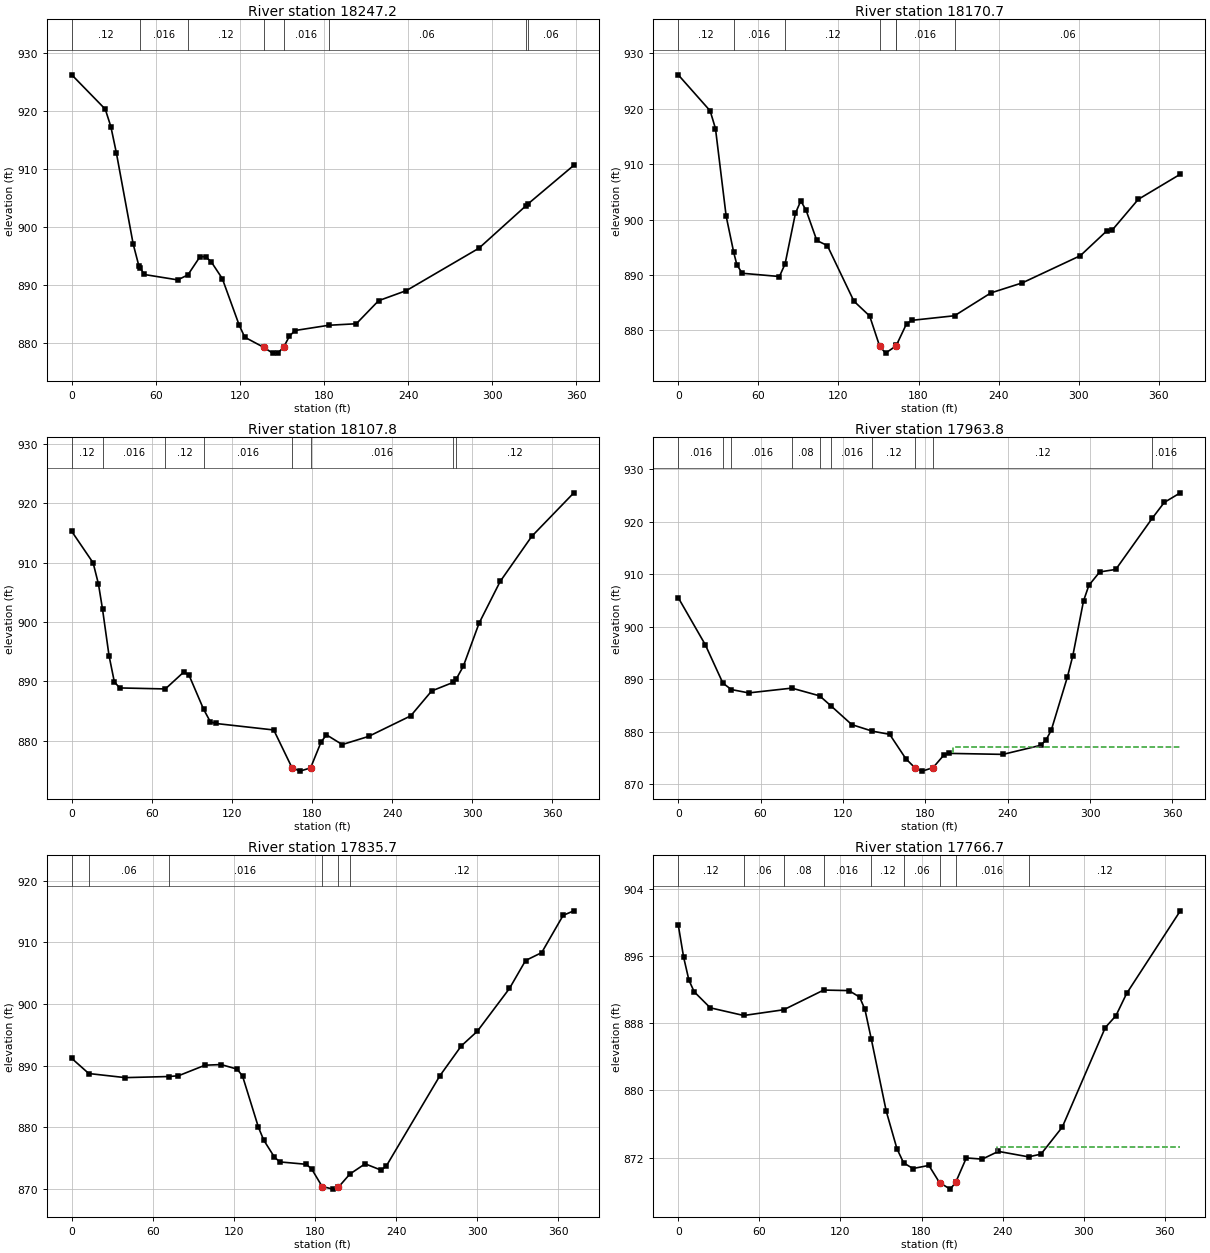
Type RM Length L Ch R = 1 ,18247.2 ,78.4,76.6,74.3
XS GIS Cut Line= 2
     2268746.791      369855.743     2269069.708      369700.795
#Sta/Elev= 30
       0  926.31    23.9  920.38    27.9  917.36    31.8  912.86    43.8  897.12
    47.8   893.4   48.87892.9748    51.7  891.85    75.6  890.92   82.82891.7748
    91.5  894.93    95.5  894.92    99.5  894.04   107.4  891.14   119.4  883.14
   123.4  881.03  136.83879.2955   143.3  878.28   147.2  878.33   151.2  879.32
   155.2  881.17   159.2  882.18   183.3883.0875     203  883.35   218.9  887.33
   238.8  889.08   290.5  896.39  323.87903.6779  325.14903.9612   358.2   910.7
#Mann= 8 ,-1 , 0
       0     .12       0   48.87    .016       0   82.82     .12       0
  136.83    .045       0   151.2    .016       0   183.3     .06       0
  323.87     .12       0  325.14     .06       0
Bank Sta=136.83,151.2
XS Rating Curve= 0 ,0
Exp/Cntr=0.3,0.1

Type RM Length L Ch R = 1 ,18170.7 ,63.1,62.9,62.8
XS GIS Cut Line= 3
     2268748.093      369880.483     2268871.791      369879.181
     2269091.843      369755.483
#Sta/Elev= 30
       0  926.14    23.9  919.64    27.9  916.43    35.9  900.62   41.58894.0698
    43.9  891.86    47.9  890.32    75.8  889.73   80.04 892.009    87.8  901.15
    91.8  903.39    95.8  901.67   103.8  896.24   111.7  895.31   131.6  885.28
   143.4   882.6  150.89877.1464   155.3   875.9   163.2  877.21  163.35  877.29
     171  881.19     175  881.82  206.96882.6472   234.2  886.77   257.8  888.59
   301.2  893.49   320.9  897.94   324.9  898.06   344.6  903.66   376.1   908.2
#Mann= 7 ,-1 , 0
       0     .12       0   41.58    .016       0   80.04     .12       0
  150.89    .045       0   163.2     .12       0  163.35    .016       0
  206.96     .06       0
Bank Sta=150.89,163.2
XS Rating Curve= 0 ,0
Exp/Cntr=0.3,0.1

Type RM Length L Ch R = 1 ,18107.8 ,125.9,144,158.1
XS GIS Cut Line= 3
      2268765.02      369942.983     2268888.718      369941.681
      2269108.77      369817.983
#Sta/Elev= 30
       0  915.26      16  909.96      20  906.38   23.03902.1613    27.9  894.33
    31.9  889.88    35.9  888.87    70.1 888.699    83.8  891.53    87.8  891.04
    98.7885.2963   103.8  883.16   107.7  882.88   151.3  881.78     165   875.4
     171  874.84   178.9  875.39   186.8  879.77   190.8  880.96   202.6  879.32
   222.3  880.69   253.9  884.16   269.6  888.36  285.54889.7911   287.8 890.294
   293.3  892.52   305.1  899.78   320.9  906.82   344.6  914.44   376.1  921.77
#Mann= 8 ,-1 , 0
       0     .12       0   23.03    .016       0    70.1     .12       0
    98.7    .016       0     165    .045       0   178.9    .016       0
  285.54     .06       0   287.8     .12       0
Bank Sta=165,178.9
XS Rating Curve= 0 ,0
Exp/Cntr=0.3,0.1

Type RM Length L Ch R = 1 ,17963.8 ,129.7,128.1,127
XS GIS Cut Line= 3
     2268747.797       370023.33     2268926.247      370057.189
     2269107.597      370088.727
#Sta/Elev= 30
       0  905.58    19.7  896.62    32.5889.3123   38.65888.0814    51.3  887.44
   82.71888.3514  102.99886.8802  111.21884.9808   126.4   881.4  141.36880.1532
     154  879.55   165.8  874.89  172.26873.2152   177.7  872.54   185.6   873.2
   193.4  875.58   197.3  875.92   236.5  875.73   263.9  877.45   267.8  878.44
   271.7  880.33   283.5  890.51   287.4  894.52   295.2  904.96   299.1  907.93
     307  910.48   318.7  910.96  345.14920.6677     354  923.72   365.7  925.55
#Mann= 10 ,-1 , 0
       0    .016       0    32.5     .12       0   38.65    .016       0
   82.71     .08       0  102.99     .06       0  111.21    .016       0
  141.36     .12       0  172.26    .045       0   185.6     .12       0
  345.14    .016       0
#XS Ineff= 2 , 0
                          199.79           877.2
Permanent Ineff=
       F       F
Bank Sta=172.26,185.6
XS Rating Curve= 0 ,0
Exp/Cntr=0.3,0.1

Type RM Length L Ch R = 1 ,17835.7 ,69.6,68.9,66
XS GIS Cut Line= 3
     2268728.562      370173.452     2269012.416       370185.17
     2269090.541      370146.108
#Sta/Elev= 30
       0  891.17   12.58888.7137    39.5  888.05   71.71888.2289    78.9  888.35
    98.6  890.07   110.5  890.17   122.3  889.43   126.3  888.32   138.1  879.97
     142   877.9   149.9  875.14   153.9  874.36   173.6  873.97   177.6  873.16
   185.2870.3642   193.3  869.94   197.3  870.27  205.71872.3876     217  874.05
   228.9  873.02   232.8  873.74   272.3  888.35   288.1  893.19     300  895.58
   323.8  902.54   335.7  907.07   347.6  908.35   363.5  914.41   371.4  915.14
#Mann= 6 ,-1 , 0
       0    .016       0   12.58     .06       0   71.71    .016       0
   185.2    .045       0   197.3    .016       0  205.71     .12       0
Bank Sta=185.2,197.3
XS Rating Curve= 0 ,0
Exp/Cntr=0.3,0.1

Type RM Length L Ch R = 1 ,17766.7 ,162.4,147.7,132.5
XS GIS Cut Line= 3
     2268723.354      370238.556     2269007.208      370250.274
     2269085.333      370211.212
#Sta/Elev= 30
       0  899.71       4  895.84     7.9  893.12    11.8  891.74    23.7  889.83
   48.45888.9169   78.02889.6006  107.59891.9436   126.3  891.88   134.2   891.1
   138.1  889.64  142.82886.1069   153.9  877.51   161.8  873.06  166.72871.3849
   173.6  870.71   185.4  871.08   193.3  869.03   201.2  868.26   205.2  869.05
   213.1  871.97   224.9  871.83   236.8  872.75  259.11872.0998   268.3  872.42
   284.1  875.64   315.9  887.48   323.8   888.9   331.7  891.54   371.4  901.37
#Mann= 9 ,-1 , 0
       0     .12       0   48.45     .06       0   78.02     .08       0
  107.59    .016       0  142.82     .12       0  166.72     .06       0
   193.3    .045       0   205.2    .016       0  259.11     .12       0
#XS Ineff= 2 , 0
                          236.12          873.24
Permanent Ineff=
       F       F
Bank Sta=193.3,205.2
XS Rating Curve= 0 ,0
Exp/Cntr=0.3,0.1

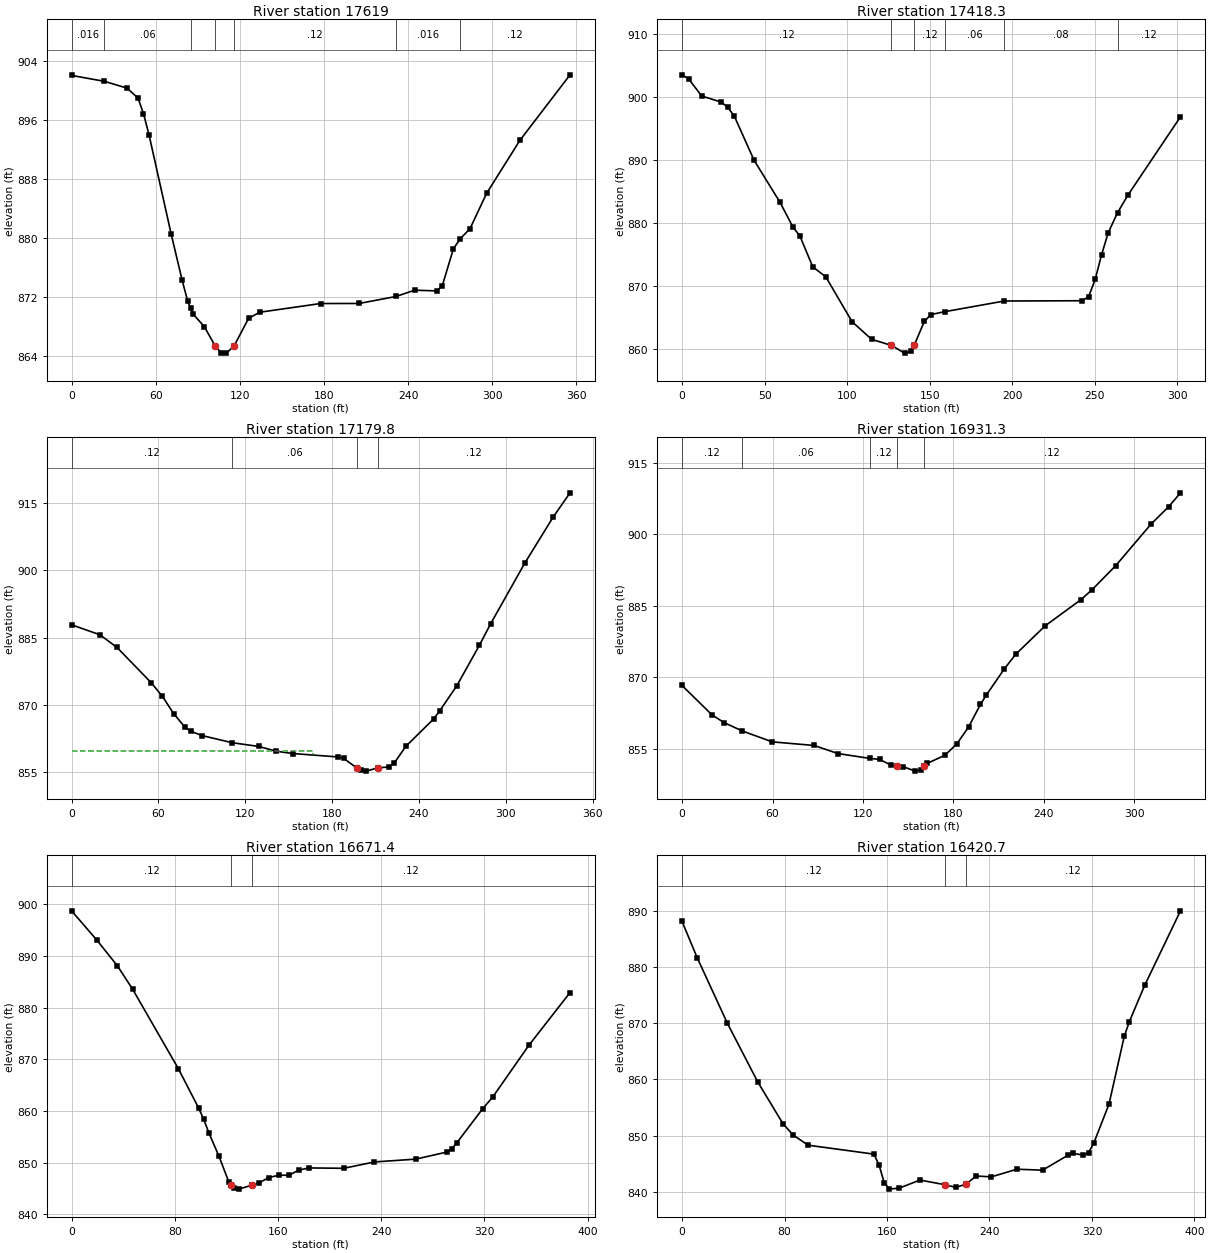
Type RM Length L Ch R = 1 ,17619   ,200.2,200.7,200.7
XS GIS Cut Line= 3
     2268844.447      370450.795     2269060.593      370298.452
     2269094.447      370213.816
#Sta/Elev= 30
       0  902.03   23.44901.2275    39.5  900.31    47.4  898.96    51.3  896.85
    55.3  893.93      71  880.57    78.9  874.25    82.9   871.4    84.9870.5128
    86.8  869.67    94.7  867.98   102.6  865.32   106.6  864.48   110.5   864.4
     116   865.4   126.3  869.12   134.2  869.94   177.6  871.12   205.2  871.13
  231.61872.0829   244.7  872.93   260.5  872.83   264.4   873.5   272.4  878.54
   277.3 879.905   284.2  881.25   296.1  886.06   319.9  893.25   355.6  902.11
#Mann= 7 ,-1 , 0
       0    .016       0   23.44     .06       0    84.9     .12       0
   102.6    .045       0     116     .12       0  231.61    .016       0
   277.3     .12       0
Bank Sta=102.6,116
XS Rating Curve= 0 ,0
Exp/Cntr=0.3,0.1

Type RM Length L Ch R = 1 ,17418.3 ,247.9,238.4,228.5
XS GIS Cut Line= 3
     2268953.822      370561.472     2269047.572      370545.847
     2269218.145       370428.66
#Sta/Elev= 30
       0  903.54       4   902.9    11.9  900.17    23.8   899.2    27.7  898.38
    31.7  896.95    43.6  889.98    59.4  883.25    67.3  879.28    71.3  877.98
    79.2  873.01    87.1  871.42     103  864.29   114.9  861.48   126.9  860.52
   134.8  859.29   138.8  859.55  140.73860.5873   146.8  864.33   150.8  865.42
  159.03865.8748  195.27867.5773   242.3  867.62   246.3  868.24   250.3     871
   254.2  874.95   258.2  878.43  263.87881.6249   270.2  884.43     302  896.87
#Mann= 6 ,-1 , 0
       0     .12       0   126.9    .045       0  140.73     .12       0
  159.03     .06       0  195.27     .08       0  263.87     .12       0
Bank Sta=126.9,140.73
XS Rating Curve= 0 ,0
Exp/Cntr=0.3,0.1

Type RM Length L Ch R = 1 ,17179.8 ,227.7,248.5,268.4
XS GIS Cut Line= 4
     2269057.989      370767.202     2269198.614      370754.181
     2269254.604      370660.431     2269335.333      370612.254
#Sta/Elev= 30
       0  887.89    19.6  885.67    31.4  882.84    54.9  875.03    62.8  871.93
    70.6  868.07    78.5  865.02    82.4  864.16    90.2  863.21  110.95 861.621
   129.5  860.78   141.2  859.73   152.9  859.21   184.1  858.45     188  858.12
  196.99856.0142   199.7   855.5   203.6  855.29   211.4  856.01   219.2  856.22
   223.1  857.17   230.9   860.8   250.4     867   254.3  868.71   266.1  874.27
   281.8  883.35   289.6  888.16   313.1  901.62   332.7  911.88   344.4   917.3
#Mann= 4 ,-1 , 0
       0     .12       0  110.95     .06       0  196.99    .045       0
   211.4     .12       0
#XS Ineff= 2 , 0
          166.87  859.81
Permanent Ineff=
       F       F
Bank Sta=196.99,211.4
XS Rating Curve= 0 ,0
Exp/Cntr=0.3,0.1

Type RM Length L Ch R = 1 ,16931.3 ,260.8,259.9,261.2
XS GIS Cut Line= 4
     2269192.104      370954.702     2269270.229      370924.754
     2269375.697      370910.431     2269465.541      370802.358
#Sta/Elev= 30
       0  868.32    19.9  862.15    27.9  860.54   39.77 858.804    59.8   856.5
    87.6  855.74   103.4  854.05  124.39853.0336     131  852.82   138.9  851.58
   142.8  851.35   146.7   851.3   154.6  850.36   158.6  850.66  160.63851.3343
   162.5  851.96   174.3  853.69   182.2  856.04   190.1  859.64   197.9  864.35
   201.8  866.31   213.5  871.69   221.3  874.87   240.9  880.85   264.3  886.26
   272.1  888.45   287.7  893.48   311.1  902.18   322.8  905.84   330.6  908.73
#Mann= 5 ,-1 , 0
       0     .12       0   39.77     .06       0  124.39     .12       0
   142.8    .045       0  160.63     .12       0
Bank Sta=142.8,160.63
XS Rating Curve= 0 ,0
Exp/Cntr=0.3,0.1

Type RM Length L Ch R = 1 ,16671.4 ,239.6,250.7,256.9
XS GIS Cut Line= 4
     2269283.249      371219.024     2269378.302      371163.035
     2269482.468       371153.92     2269597.052      371026.316
#Sta/Elev= 30
       0  898.72    19.7  893.02    35.5  888.08    47.3  883.56    82.7  868.21
    98.5  860.56   102.4   858.4   106.4  855.78   114.2  851.26   121.9  846.26
  123.89845.6324   125.8  845.03   129.7  844.88     140  845.67   145.2  846.08
   152.9  847.12   160.7  847.58   168.4  847.55   176.2  848.56   183.9  848.98
     211  848.91   234.8  850.14   266.7  850.68   290.7  852.04   294.6  852.64
   298.6  853.83   318.6  860.41   326.6  862.74   354.5  872.71   386.4  882.91
#Mann= 3 ,-1 , 0
       0     .12       0  123.89    .045       0     140     .12       0
Bank Sta=123.89,140
XS Rating Curve= 0 ,0
Exp/Cntr=0.3,0.1

Type RM Length L Ch R = 1 ,16420.7 ,286.9,302.1,314.7
XS GIS Cut Line= 4
     2269275.437      371284.129     2269383.913      371355.509
     2269518.927      371390.899     2269603.562      371475.535
#Sta/Elev= 30
       0  888.07    11.8  881.63    35.4  869.96      59  859.58    78.7  852.15
    86.6  850.13    98.4   848.3   149.8  846.71   153.8  844.77   157.8  841.65
   161.8  840.49   169.7  840.68   185.7   842.1   205.6  841.26   213.6   840.8
   221.6  841.36   229.6  842.82   241.5  842.67   261.4  844.03   281.4  843.86
   301.4  846.53   305.3  846.85   313.3  846.53   317.3  846.98   321.3  848.61
   333.3   855.6   345.2  867.64   349.2  870.27   361.2  876.73   389.1  889.95
#Mann= 3 ,-1 , 0
       0     .12       0   205.6    .045       0   221.6     .12       0
Bank Sta=205.6,221.6
XS Rating Curve= 0 ,0
Exp/Cntr=0.3,0.1

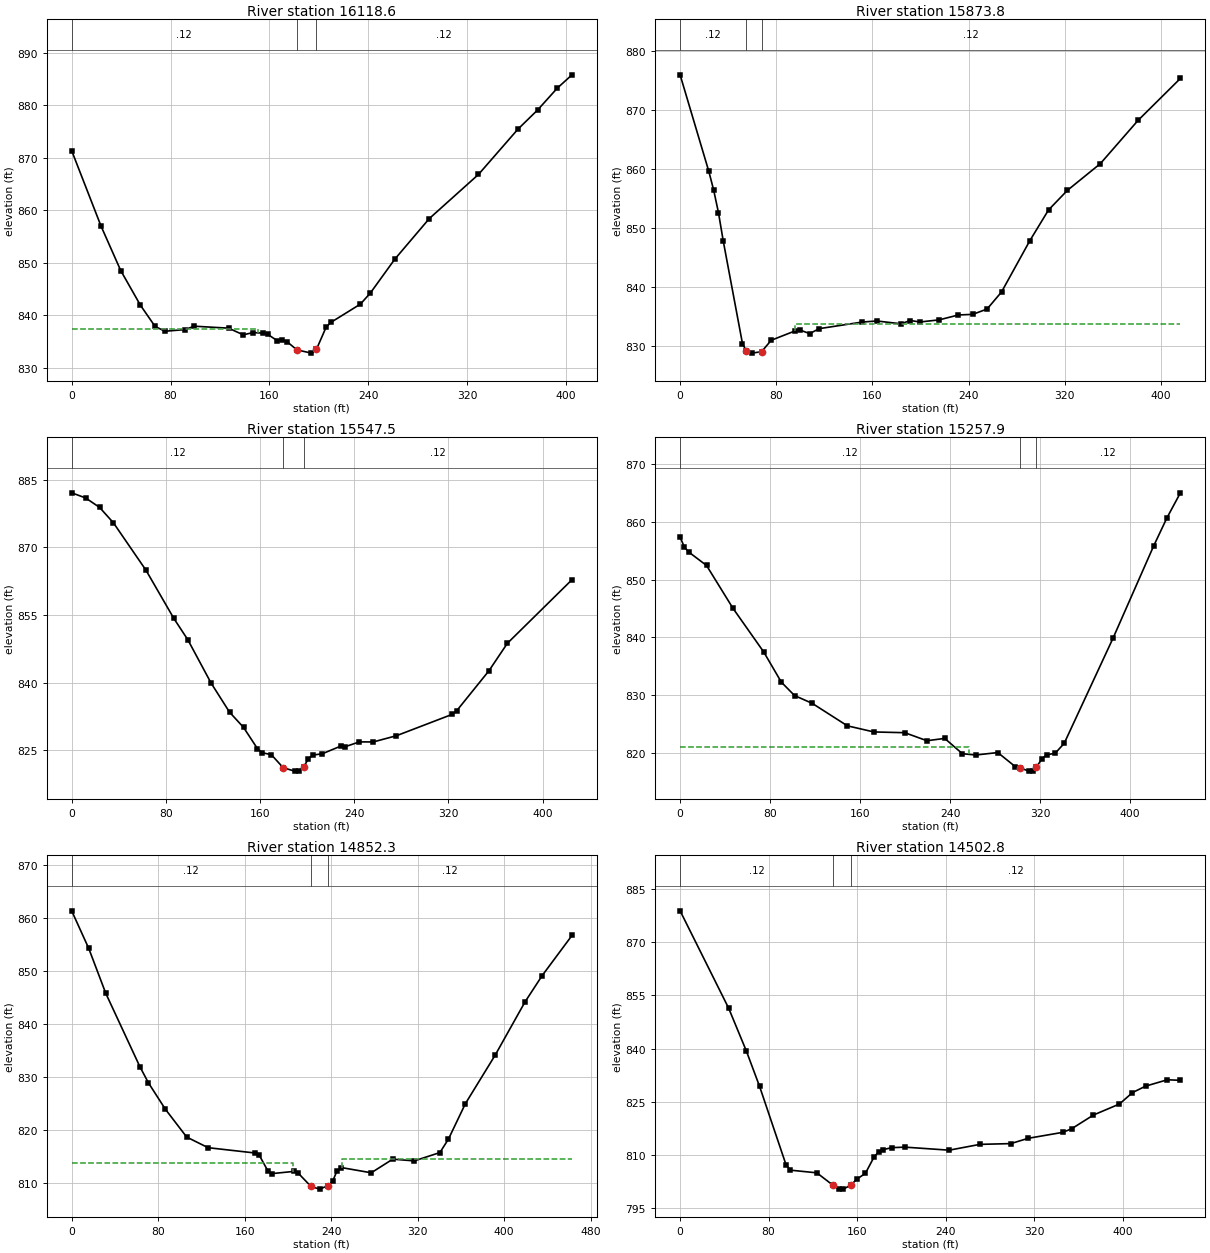
Type RM Length L Ch R = 1 ,16118.6 ,262.1,244.7,225.3
XS GIS Cut Line= 4
     2269151.739      371496.368     2269250.595      371547.362
     2269324.916      371629.181     2269505.906      371657.827
#Sta/Elev= 30
       0  871.34    23.8  856.94    39.7  848.49    55.6   841.9    67.5  837.84
    75.5  836.92    91.4  837.23    99.3  837.88     127  837.51   138.9  836.24
   146.8  836.67   154.7  836.56   158.6  836.34   166.5  835.11   170.4  835.26
   174.4  834.92   182.3  833.37   194.1  832.75   198.1  833.45     206  837.71
   209.9  838.62   233.7  842.09   241.7  844.18   261.6  850.67   289.5   858.4
   329.3  866.81   361.2  875.43   377.1  879.08   393.1  883.26     405   885.8
#Mann= 3 ,-1 , 0
       0     .12       0   182.3    .045       0   198.1     .12       0
#XS Ineff= 2 , 0
          151.19   837.4
Permanent Ineff=
       F       F
Bank Sta=182.3,198.1
XS Rating Curve= 0 ,0
Exp/Cntr=0.3,0.1

Type RM Length L Ch R = 1 ,15873.8 ,342.6,326.3,310.6
XS GIS Cut Line= 3
     2269060.593      371754.181      2269327.52      371769.806
     2269470.749      371729.441
#Sta/Elev= 30
       0  876.03    23.9  859.65    27.9  856.51    31.9  852.68    35.9  847.85
    51.9  830.45   55.22829.1564    59.9  828.84    67.8  829.09    75.8  831.02
    95.8  832.62    99.8  832.75   107.8  832.15   115.7  832.99   151.6  834.11
   163.6  834.29   183.6  833.82   191.6  834.37   199.5  834.12   215.5  834.48
   231.5  835.31   243.4  835.41   255.4  836.32   267.4  839.21   290.9  847.89
   306.5  853.12   322.2  856.44   349.6  860.97     381  868.31   416.2  875.42
#Mann= 3 ,-1 , 0
       0     .12       0   55.22    .045       0    67.8     .12       0
#XS Ineff= 2 , 0
                           95.98          833.78
Permanent Ineff=
       F       F
Bank Sta=55.22,67.8
XS Rating Curve= 0 ,0
Exp/Cntr=0.3,0.1

Type RM Length L Ch R = 1 ,15547.5 ,272.3,289.6,305
XS GIS Cut Line= 4
     2269093.145      372074.493      2269227.26      372077.097
     2269362.677      371969.024     2269479.864      371958.608
#Sta/Elev= 30
       0   882.1    11.8  880.97    23.7  878.87    35.5  875.44    63.1  864.95
    86.8  854.25    98.6  849.56   118.4  839.94   134.1  833.48     146   830.1
   157.8   825.4   161.7  824.49   169.6  824.06  179.62821.1827   189.3  820.41
   193.2  820.46   197.1  821.32   201.1   823.2     205  823.97   212.9  824.26
   228.6  825.96   232.6  825.85   244.4  826.89   256.2  826.88   275.9  828.26
   323.1  832.98     327  833.77   354.5  842.67   370.1  848.74     425  862.84
#Mann= 3 ,-1 , 0
       0     .12       0  179.62    .045       0   197.1     .12       0
Bank Sta=179.62,197.1
XS Rating Curve= 0 ,0
Exp/Cntr=0.3,0.1

Type RM Length L Ch R = 1 ,15257.9 ,387,405.6,419.1
XS GIS Cut Line= 4
     2269116.583      372166.941     2269253.302      372258.087
     2269449.916      372265.899     2269529.343      372291.941
#Sta/Elev= 30
       0  857.36     3.9  855.59     7.8  854.76    23.5  852.45      47  845.03
    74.3  837.47      90  832.23   101.7  829.91   117.4  828.56   148.7  824.66
   172.2   823.6   199.7  823.47   219.4  822.08   235.2  822.48   250.9  819.83
   262.7   819.6   282.4  820.03   298.1  817.56     302   817.4   309.9  816.81
   313.9  816.84   316.5817.4534   321.7  818.96   325.7  819.61   333.5  819.93
   341.4  821.62     385  839.93   420.8  855.78   432.7  860.69   444.7  865.04
#Mann= 3 ,-1 , 0
       0     .12       0     302    .045       0   316.5     .12       0
#XS Ineff= 2 , 0
          256.97  821.05
Permanent Ineff=
       F       F
Bank Sta=302,316.5
XS Rating Curve= 0 ,0
Exp/Cntr=0.3,0.1

Type RM Length L Ch R = 1 ,14852.3 ,374.1,349.6,323.1
XS GIS Cut Line= 4
     2268930.385      372415.639     2269080.124      372465.118
     2269203.822      372565.379     2269349.656      372564.077
#Sta/Elev= 30
       0  861.37    15.8  854.28    31.5  845.84    63.1  831.99      71  828.95
    86.7  823.97   106.4  818.73   126.2  816.73   169.6  815.73   173.6  815.28
   181.6  812.31   185.6  811.85   205.5  812.26   209.4  811.96   221.4  809.42
   229.4  808.92   237.3  809.59   241.3  810.36   245.3  812.29   249.3  812.99
   277.1     812     297  814.57   316.9  814.24   340.6  815.81   348.5  818.34
   364.2  825.03   391.8  834.19   419.4  844.22   435.2  849.16   462.8  856.73
#Mann= 3 ,-1 , 0
       0     .12       0   221.4    .045       0   237.3     .12       0
#XS Ineff= 2 , 0
          204.33  813.83  249.74          814.66
Permanent Ineff=
       F       F
Bank Sta=221.4,237.3
XS Rating Curve= 0 ,0
Exp/Cntr=0.3,0.1

Type RM Length L Ch R = 1 ,14502.8 ,197.7,197.6,195.1
XS GIS Cut Line= 3
      2268921.27      372836.212     2269177.781      372707.306
     2269341.843      372689.077
#Sta/Elev= 30
       0   878.8    43.9  851.37    59.8  839.39    71.8  829.39    95.7  807.32
    99.7  805.76   123.6  805.01   138.2801.5165   143.5  800.46   147.5  800.42
  154.23 801.526   159.5  803.16   167.5  804.88   175.4  809.52   179.4  810.88
   183.4  811.53   191.4  812.11   203.4  812.24   243.2  811.39   271.1  813.03
   298.9  813.24   314.6  814.73     346  816.42   353.9  817.42   373.6  821.29
   397.1  824.39   408.9  827.61   420.7  829.42   440.4  831.22   452.2  831.06
#Mann= 3 ,-1 , 0
       0     .12       0   138.2    .045       0  154.23     .12       0
Bank Sta=138.2,154.23
XS Rating Curve= 0 ,0
Exp/Cntr=0.3,0.1