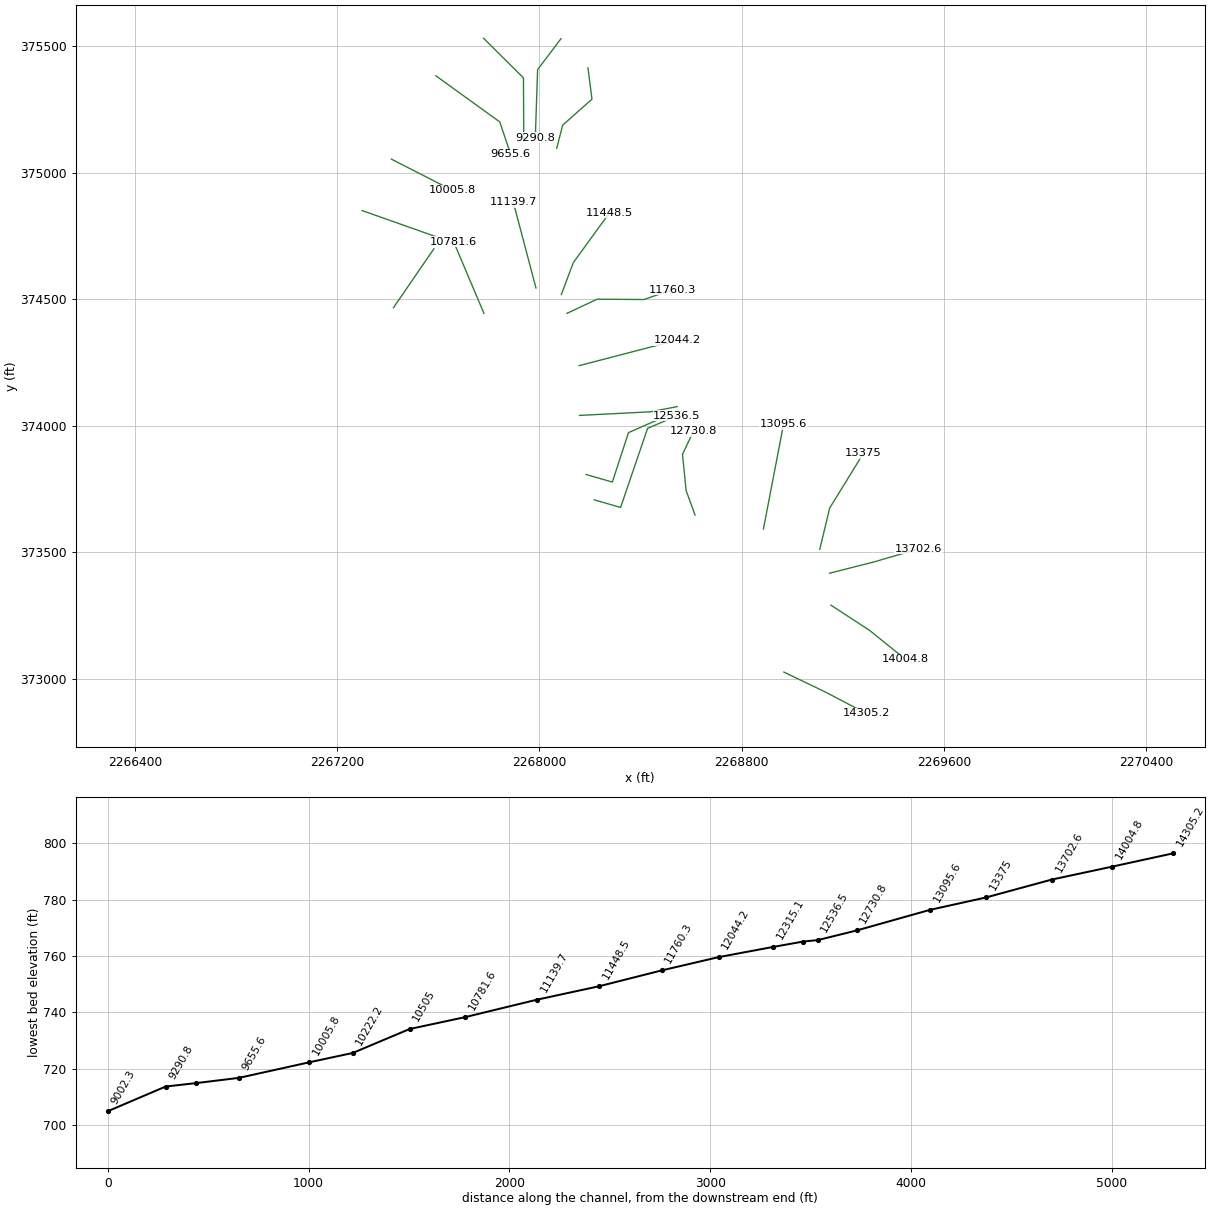
HEC-RAS study BIGRUN1.prj: BIGRUN1

--- BIGRUN1.g01 (geometry) --- (continued)

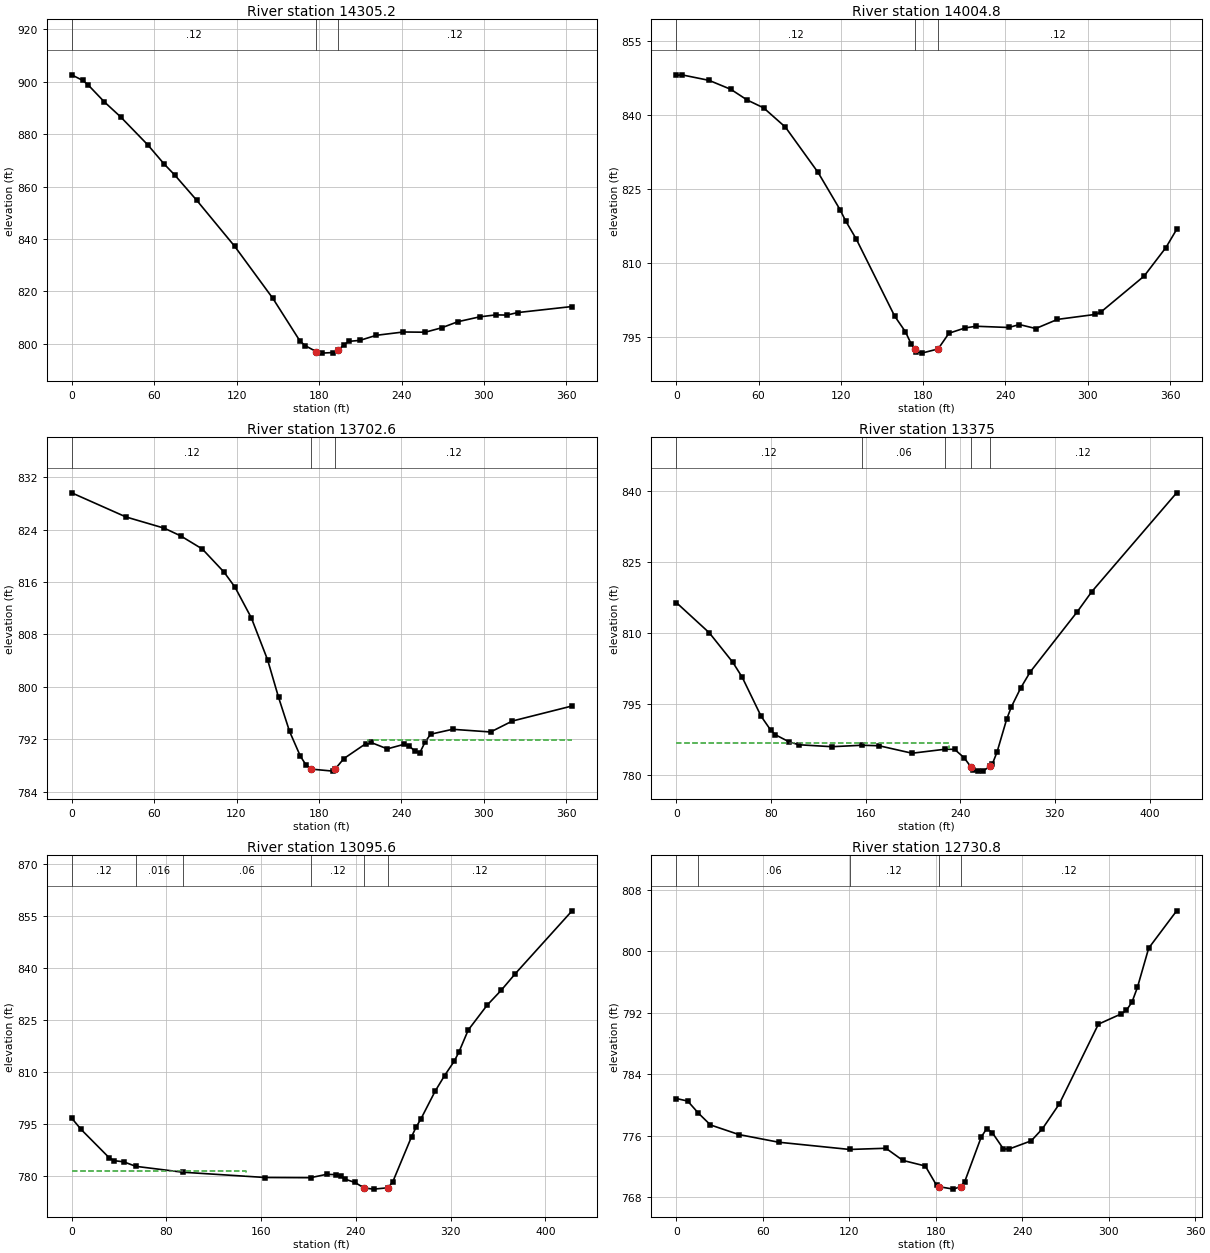
Type RM Length L Ch R = 1 ,14305.2 ,302.8,300.4,296.3
XS GIS Cut Line= 3
     2268966.868      373026.709     2269130.902      372947.913
     2269292.308      372863.544
#Sta/Elev= 30
       0  902.63     7.9  900.53    11.9  898.82    23.7  892.33    35.6  886.58
    55.4  875.88    67.2  868.63    75.2  864.26      91  854.73   118.7  837.11
   146.4  817.29   166.2  800.95   170.1  799.19     178  796.98     182   796.4
   189.9  796.62   193.9  797.44   197.8  799.51   201.8   800.9   209.7  801.26
   221.6   803.2   241.4  804.47   257.2  804.38   269.1  806.05     281  808.39
   296.8  810.24   308.7     811   316.6  810.92   324.5  811.88   364.1  814.19
#Mann= 3 ,-1 , 0
       0     .12       0     178    .045       0   193.9     .12       0
Bank Sta=178,193.9
XS Rating Curve= 0 ,0
Exp/Cntr=0.3,0.1

Type RM Length L Ch R = 1 ,14004.8 ,281.6,302.1,323.6
XS GIS Cut Line= 3
     2269152.711      373291.154     2269306.059      373191.227
     2269447.596      373077.095
#Sta/Elev= 30
       0  847.95       4  848.07    23.9  846.95    39.8  845.13    51.7  842.97
    63.7  841.38    79.6  837.47   103.4   828.3   119.4  820.77   123.4  818.54
   131.3  814.78   159.2  799.23   167.1  796.04   171.1  793.67  173.75792.5967
   175.1  792.05     179  791.73   190.9  792.58   198.8  795.76   210.7  796.84
   218.6  797.17   242.3  796.92   250.2  797.51   262.1  796.71   277.9  798.56
   305.6  799.57   309.5  800.03   341.1  807.33     357  813.11   364.8  816.78
#Mann= 3 ,-1 , 0
       0     .12       0  173.75    .045       0   190.9     .12       0
Bank Sta=173.75,190.9
XS Rating Curve= 0 ,0
Exp/Cntr=0.3,0.1

Type RM Length L Ch R = 1 ,13702.6 ,309,327.6,342.7
XS GIS Cut Line= 3
     2269147.575      373417.435     2269324.307      373462.323
     2269498.927      373513.412
#Sta/Elev= 30
       0  829.63    39.6  825.94    67.4  824.23    79.3  823.06    95.1  821.05
     111   817.5   118.9  815.22   130.8  810.53   142.7  804.08   150.6   798.4
   158.6   793.2   166.5   789.4   170.4  788.13   174.4  787.43   190.2  787.12
  191.76 787.432   198.2  789.04     214   791.3   217.9   791.5   229.8  790.52
   241.7   791.2   245.6     791   249.6  790.21   253.5  789.94   257.5  791.64
   261.4  792.76   277.3  793.51     305   793.1   320.8  794.77   364.3  797.07
#Mann= 3 ,-1 , 0
       0     .12       0   174.4    .045       0  191.76     .12       0
#XS Ineff= 2 , 0
                          215.48          791.91
Permanent Ineff=
       F       F
Bank Sta=174.4,191.76
XS Rating Curve= 0 ,0
Exp/Cntr=0.3,0.1

Type RM Length L Ch R = 1 ,13375   ,270.7,279.4,287.3
XS GIS Cut Line= 3
      2269108.77      373511.993     2269147.833      373674.754
     2269281.947      373892.202
#Sta/Elev= 30
       0  816.38    27.9  809.99    47.8  803.75    55.8  800.56    71.7  792.36
    79.7  789.47    83.7  788.46    95.6  786.92   103.6  786.34   131.5  785.93
  156.88786.2356   171.4  786.13   199.3  784.55  227.05785.3925   235.2  785.37
   243.2  783.62  248.89781.7061   251.2  780.99   255.2  780.77   259.2  780.81
  265.19 781.764   267.2   782.3   271.2  784.88   279.2   791.7   283.2  794.34
   291.1  798.33   299.1  801.71     339  814.46     351  818.62   422.9  839.55
#Mann= 5 ,-1 , 0
       0     .12       0  156.88     .06       0  227.05     .12       0
  248.89    .045       0  265.19     .12       0
#XS Ineff= 2 , 0
          230.65  786.69
Permanent Ineff=
       F       F
Bank Sta=248.89,265.19
XS Rating Curve= 0 ,0
Exp/Cntr=0.3,0.1

Type RM Length L Ch R = 1 ,13095.6 ,358,364.8,371.1
XS GIS Cut Line= 2
     2268885.809       373591.94     2268965.648      374006.859
#Sta/Elev= 30
       0  796.81       8  793.54    31.9  785.32    35.9  784.55    43.8  784.24
   54.14782.9269   93.82 781.234   163.4  779.71  201.68779.6514   215.2  780.62
   223.2  780.53   227.2  780.06   231.2   779.2   239.2  778.27   247.1  776.67
   255.1  776.36   267.1  776.75   271.1  778.45     287  791.48     291  794.34
     295  796.66   306.9  804.58   314.9  809.09   322.9  813.16   326.9  815.79
   334.8  822.18   350.8  829.36   362.7  833.66   374.7  838.48   422.5  856.54
#Mann= 6 ,-1 , 0
       0     .12       0   54.14    .016       0   93.82     .06       0
  201.68     .12       0   247.1    .045       0   267.1     .12       0
#XS Ineff= 2 , 0
          147.06  781.62
Permanent Ineff=
       F       F
Bank Sta=247.1,267.1
XS Rating Curve= 0 ,0
Exp/Cntr=0.3,0.1

Type RM Length L Ch R = 1 ,12730.8 ,203.7,194.3,184.3
XS GIS Cut Line= 5
     2268615.281       373647.41     2268580.305      373743.782
     2268572.066      373825.381     2268565.864      373886.868
      2268608.77      373978.139
#Sta/Elev= 30
       0  780.85     7.9  780.52   15.34778.9454    23.7  777.41    43.4  776.16
      71  775.16  120.25774.2166   145.5  774.37   157.2  772.79   172.8  772.06
   180.6  769.55   182.4769.3647   192.3  769.05   197.4769.3824     200  769.95
   211.6  775.83   215.4  776.93   219.3   776.4     227  774.28   230.9  774.27
   246.3  775.34   254.1  776.92   265.7  780.12   292.9  790.53   308.4  791.84
   312.3  792.33   316.2   793.4     320  795.33   327.8  800.43   347.2  805.29
#Mann= 5 ,-1 , 0
       0    .016       0   15.34     .06       0  120.25     .12       0
   182.4    .045       0   197.4     .12       0
Bank Sta=182.4,197.4
XS Rating Curve= 0 ,0
Exp/Cntr=0.3,0.1

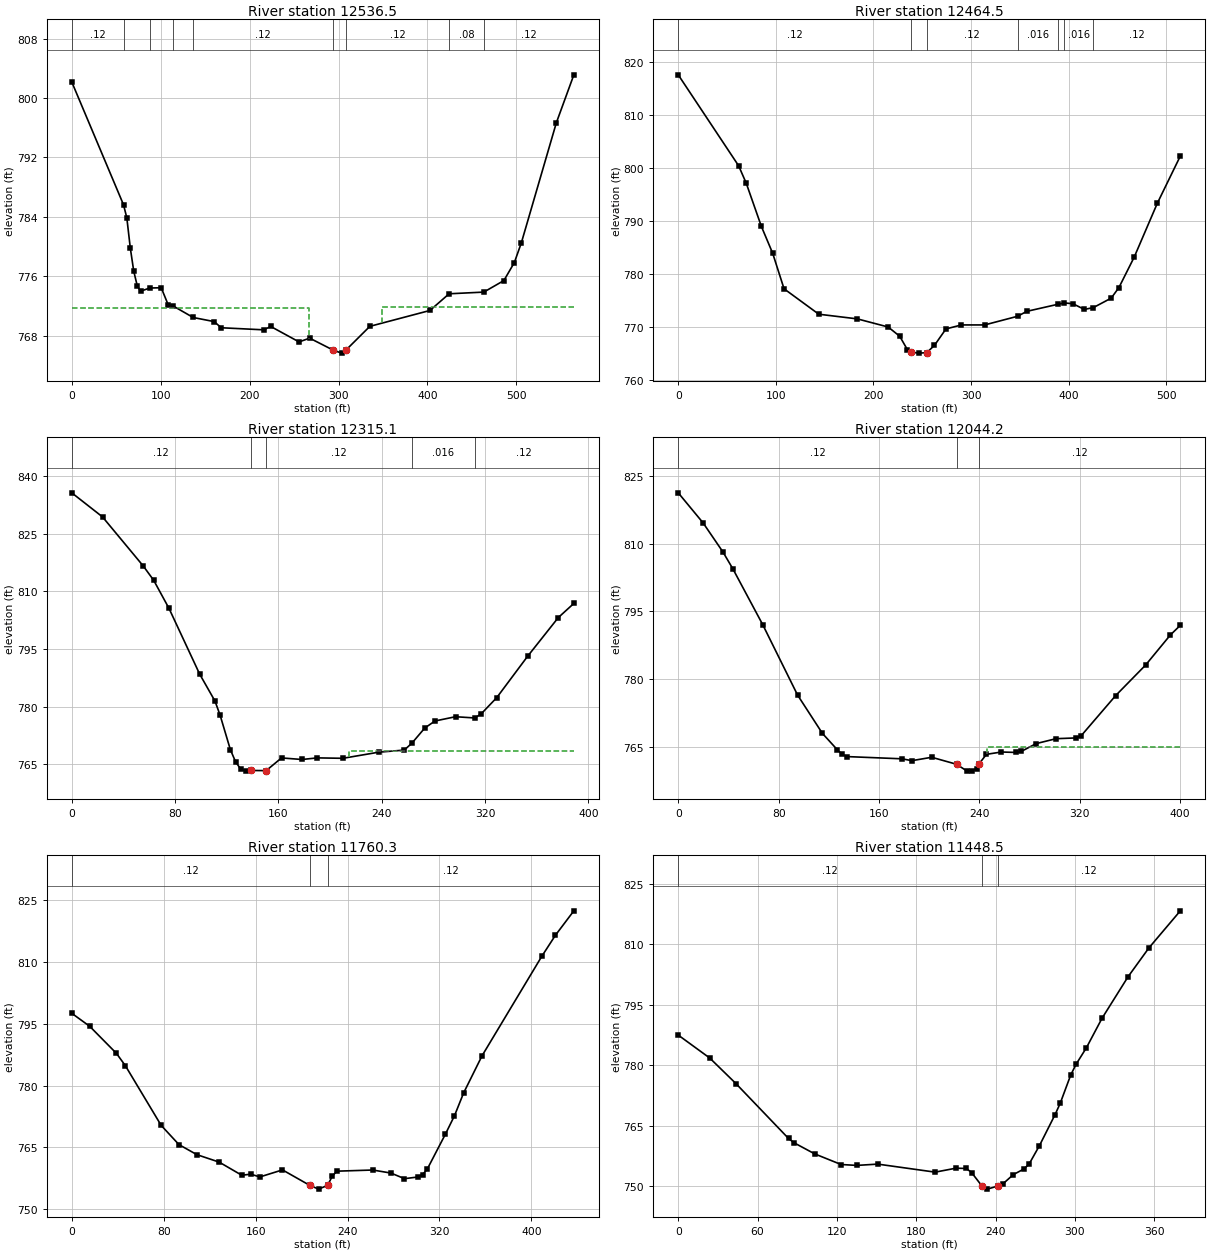
Type RM Length L Ch R = 1 ,12536.5 ,70.3,72,75.1
XS GIS Cut Line= 4
     2268216.843      373707.306      2268321.01      373677.358
     2268427.781      373989.858     2268543.666      374039.337
#Sta/Elev= 30
       0  802.18   58.19785.6274    61.9  783.87    65.8  779.82    69.7  776.67
    73.6  774.72    77.4  773.97   87.58774.4064   100.6  774.44   108.4  772.15
  114.08771.9786  136.52770.4332   160.1  769.88   168.1  769.05   215.8  768.77
   223.8  769.22   255.6  767.14   267.5  767.65   293.9  766.04   303.4  765.63
   308.9  766.11   335.2  769.24   402.8  771.38  424.31773.6282  463.34773.8557
   485.9  775.41   497.7  777.84   505.6  780.51   544.9  796.67   564.6  803.14
#Mann= 9 ,-1 , 0
       0     .12       0   58.19    .016       0   87.58     .06       0
  114.08    .016       0  136.52     .12       0   293.9    .045       0
   308.9     .12       0  424.31     .08       0  463.34     .12       0
#XS Ineff= 2 , 0
          266.25  771.66  348.61          771.82
Permanent Ineff=
       F       F
Bank Sta=293.9,308.9
XS Rating Curve= 0 ,0
Exp/Cntr=0.3,0.1

Type RM Length L Ch R = 1 ,12464.5 ,176.7,149.5,118.3
XS GIS Cut Line= 4
     2268184.291      373807.566     2268288.458      373777.618
      2268352.26      373972.931     2268535.854       374053.66
#Sta/Elev= 30
       0  817.54    61.9   800.4    69.7  797.11    85.2  788.98    96.8  783.91
   108.4  777.24     144  772.45   183.5  771.57   215.1  770.04   226.9   768.3
   234.8  765.77   238.8  765.28   246.7  765.12   254.6  765.21   262.5  766.58
   274.3  769.68   290.2  770.43   313.9  770.43  347.79772.0681   357.1  772.99
     389774.3205  395.45774.5756   404.3  774.43   416.1  773.35  425.43773.7083
   443.6  775.48   451.5  777.47   467.2  783.22   490.8  793.33   514.4  802.24
#Mann= 7 ,-1 , 0
       0     .12       0   238.8    .045       0   254.6     .12       0
  347.79    .016       0     389     .08       0  395.45    .016       0
  425.43     .12       0
Bank Sta=238.8,254.6
XS Rating Curve= 0 ,0
Exp/Cntr=0.3,0.1

Type RM Length L Ch R = 1 ,12315.1 ,265.5,270.9,275.2
XS GIS Cut Line= 3
     2268158.629         374041.     2268439.484      374055.266
     2268544.968      374075.795
#Sta/Elev= 30
       0   835.7    23.8  829.43    55.4  816.62    63.4  812.93    75.3  805.58
      99  788.49   110.9  781.44   114.9  777.71   122.8  768.78   126.8  765.66
   130.7  763.77   134.7  763.21   138.6  763.38   150.5  763.34   162.4  766.65
   178.2  766.24   190.1  766.66   209.9  766.55   237.6  768.14   257.4  768.69
  263.33770.4927   273.3  774.44   281.2  776.27   297.1  777.38  312.05777.0579
     317  778.14     329  782.35   352.9  793.12   376.7  803.22   388.7  806.89
#Mann= 5 ,-1 , 0
       0     .12       0   138.6    .045       0   150.5     .12       0
  263.33    .016       0  312.05     .12       0
#XS Ineff= 2 , 0
                          214.65          768.38
Permanent Ineff=
       F       F
Bank Sta=138.6,150.5
XS Rating Curve= 0 ,0
Exp/Cntr=0.3,0.1

Type RM Length L Ch R = 1 ,12044.2 ,288.7,283.9,273.3
XS GIS Cut Line= 2
     2268157.151      374237.658      2268544.42      374338.247
#Sta/Elev= 30
       0  821.29    19.8  814.63    35.6  808.19    43.6  804.41    67.4  792.03
    95.1  776.46   114.9  767.96   126.8  764.33   130.7   763.3   134.7  762.82
   178.3  762.33   186.2  761.92     202  762.67   221.8  761.12   229.8  759.67
   233.7   759.6   237.7  760.18   239.9  761.28   245.6  763.32   257.5  763.84
   269.4  763.74   273.4  763.97   285.2   765.7   301.1  766.79   316.9  766.96
   320.9  767.38   348.6  776.35   372.4   783.1   392.2  789.79   400.1  791.92
#Mann= 3 ,-1 , 0
       0     .12       0   221.8    .045       0   239.9     .12       0
#XS Ineff= 2 , 0
                          246.13          764.86
Permanent Ineff=
       F       F
Bank Sta=221.8,239.9
XS Rating Curve= 0 ,0
Exp/Cntr=0.3,0.1

Type RM Length L Ch R = 1 ,11760.3 ,289,311.8,332.9
XS GIS Cut Line= 4
      2268108.77      374444.285     2268228.562      374500.274
     2268413.458      374498.972     2268526.739      374538.035
#Sta/Elev= 30
       0  797.58    15.6  794.42    38.9  787.84    46.7  784.83    77.8  770.36
    93.3  765.69   108.9  763.25   128.3  761.44     148  758.25   155.8  758.51
   163.7  757.84   183.4  759.55     207  755.82   214.8  754.88   222.7   755.8
   226.6  757.95   230.6  759.24     262  759.52   277.8  758.78   289.6  757.42
   301.4  757.83   305.3  758.42   309.3  759.68   325.1  768.17   333.1   772.7
   341.1  778.26   357.1  787.26     409  811.37     421  816.54     437  822.46
#Mann= 3 ,-1 , 0
       0     .12       0     207    .045       0   222.7     .12       0
Bank Sta=207,222.7
XS Rating Curve= 0 ,0
Exp/Cntr=0.3,0.1

Type RM Length L Ch R = 1 ,11448.5 ,288.4,308.8,328.2
XS GIS Cut Line= 3
     2268086.635      374518.504     2268134.081      374644.984
     2268278.041      374842.722
#Sta/Elev= 30
       0  787.44    23.8  781.76    43.7   775.4    83.4  761.82    87.4  760.78
   103.3  757.98   123.2  755.36   135.1  755.14   150.9  755.46   194.3  753.47
     210  754.45   217.9  754.38   221.9  753.35   229.8  749.98   233.7  749.26
   241.6  750.02   245.6  750.58   253.4  752.86   261.3  754.23   265.3  755.45
   273.2  760.06     285  767.74   288.9  770.56   296.8  777.53   300.8  780.17
   308.7  784.31   320.5  791.61   340.2  801.91     356  809.07   379.7  818.24
#Mann= 3 ,-1 , 0
       0     .12       0   229.8    .045       0   241.6     .12       0
Bank Sta=229.8,241.6
XS Rating Curve= 0 ,0
Exp/Cntr=0.3,0.1

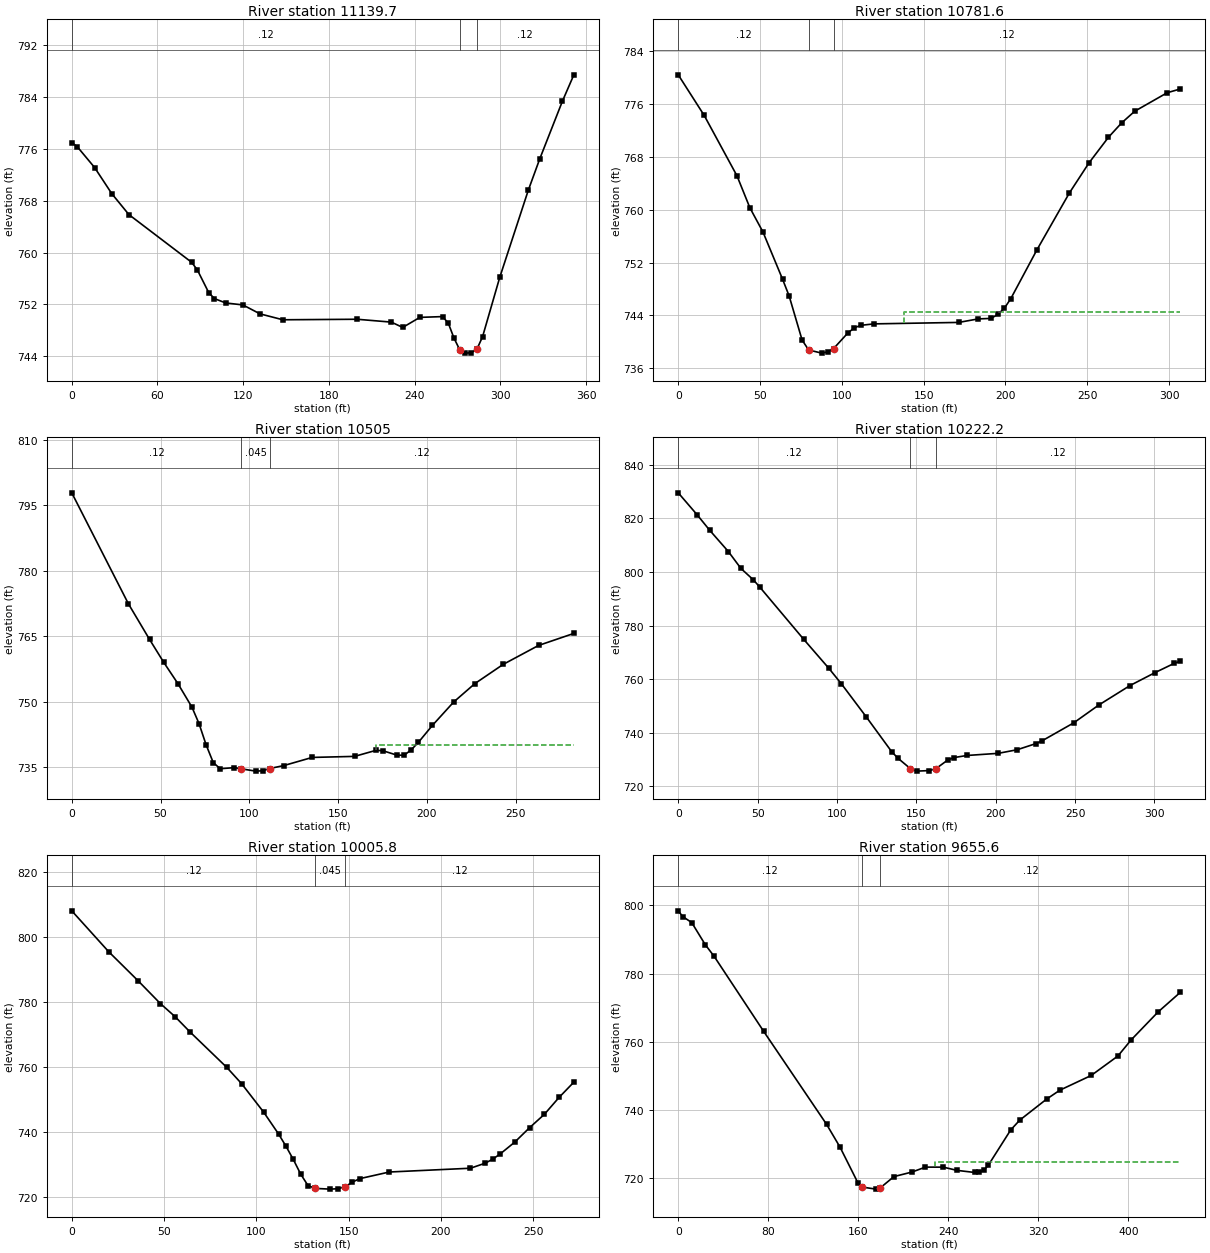
Type RM Length L Ch R = 1 ,11139.7 ,353.8,358.1,360.6
XS GIS Cut Line= 2
     2267986.374      374544.545     2267896.531      374884.389
#Sta/Elev= 30
       0  776.96       4  776.27      16   773.1      28  769.08      40  765.85
    83.9   758.5    87.9  757.33    95.9  753.82    99.9   752.9   107.8  752.23
   119.8  751.93   131.8  750.55   147.8  749.64   199.7  749.72   223.7  749.28
   231.7  748.46   243.7  750.01   259.6  750.13   263.6  749.12   267.6  746.81
   271.6  745.02   275.6   744.5   279.6  744.56   283.6  745.09   287.6  747.03
   299.6  756.16   319.6   769.6   327.6  774.42   343.5  783.33   351.5  787.39
#Mann= 3 ,-1 , 0
       0     .12       0   271.6    .045       0   283.6     .12       0
Bank Sta=271.6,283.6
XS Rating Curve= 0 ,0
Exp/Cntr=0.3,0.1

Type RM Length L Ch R = 1 ,10781.6 ,299.8,276.6,243.1
XS GIS Cut Line= 2
     2267780.645      374444.285     2267660.854      374726.837
#Sta/Elev= 30
       0  780.45    15.9  774.29    35.9  765.16    43.8  760.31    51.8  756.64
    63.8  749.48    67.8  746.95    75.7  740.29    79.7  738.78    87.7   738.3
    91.7  738.52      95     739   103.6  741.33   107.6  742.13   111.6  742.51
   119.6  742.73   171.4  742.95   183.3  743.48   191.3  743.56   195.3  744.17
   199.3  745.08   203.3  746.56   219.2  753.92   239.1  762.56   251.1  767.12
     263     771     271  773.16     279  774.93   298.9  777.74   306.9  778.31
#Mann= 3 ,-1 , 0
       0     .12       0    79.7    .045       0      95     .12       0
#XS Ineff= 2 , 0
                          137.98          744.49
Permanent Ineff=
       F       F
Bank Sta=79.7,95
XS Rating Curve= 0 ,0
Exp/Cntr=0.3,0.1

Type RM Length L Ch R = 1 ,10505   ,311.9,282.8,261.2
XS GIS Cut Line= 2
     2267422.572       374466.42     2267582.729      374699.493
#Sta/Elev= 30
       0  797.88    31.9  772.44    43.8  764.28    51.8  759.02    59.8  754.13
    67.7  748.74    71.7  744.95    75.7  740.07    79.7  736.04    83.6  734.63
    91.6  734.88    95.6   734.6   103.6  734.08   107.5  734.16   111.5  734.68
   119.5  735.36   135.4  737.22   159.3  737.46   171.3  738.84   175.2  738.76
   183.2  737.74   187.2  737.72   191.2  738.96   195.2  740.66   203.1  744.55
   215.1  749.92     227  754.13     243  758.55   262.9  762.89   282.8  765.65
#Mann= 3 ,-1 , 0
       0     .12       0    95.6    .045       0   111.5     .12       0
#XS Ineff= 2 , 0
                          171.21          740.05
Permanent Ineff=
       F       F
Bank Sta=95.6,111.5
XS Rating Curve= 0 ,0
Exp/Cntr=0.3,0.1

Type RM Length L Ch R = 1 ,10222.2 ,217.7,216.4,212.5
XS GIS Cut Line= 2
     2267298.874      374850.535     2267597.052      374745.066
#Sta/Elev= 30
       0  829.59    11.9  821.39    19.8  815.61    31.6  807.63    39.5  801.33
    47.4  797.03    51.4  794.34    79.1  774.81    94.9     764   102.8  758.21
   118.6  745.74   134.4  732.91   138.4  730.42   146.3   726.5   150.2  725.59
   158.1  725.79   162.1  726.41     170  729.83     174  730.68   181.9  731.44
   201.6  732.24   213.5  733.58   225.4  735.89   229.3  736.94   249.1  743.61
   264.9  750.28   284.6  757.57   300.5  762.44   312.3  765.82   316.3  766.69
#Mann= 3 ,-1 , 0
       0     .12       0   146.3    .045       0   162.1     .12       0
Bank Sta=146.3,162.1
XS Rating Curve= 0 ,0
Exp/Cntr=0.3,0.1

Type RM Length L Ch R = 1 ,10005.8 ,354,350.3,346.3
XS GIS Cut Line= 2
      2267414.76       375053.66     2267656.947      374929.962
#Sta/Elev= 30
       0  808.15      20  795.54      36  786.53      48  779.53      56  775.48
      64  770.81      84  759.83      92  754.82     104     746     112  739.32
     116  735.56     120  731.45     124  726.93     128  723.35     132   722.5
     140  722.28     144   722.4     148  722.98     152  724.44     156  725.51
     172  727.56     216  728.73     224  730.29     228  731.51     232  733.09
     240  736.79     248  741.23     256  745.34     264  750.58     272  755.29
#Mann= 3 ,-1 , 0
       0     .12       0     132    .045       0     148     .12       0
Bank Sta=132,148
XS Rating Curve= 0 ,0
Exp/Cntr=0.3,0.1

Type RM Length L Ch R = 1 ,9655.6  ,215.9,212.2,208.6
XS GIS Cut Line= 3
     2267590.541      375383.087     2267843.145      375200.795
     2267886.114      375073.191
#Sta/Elev= 30
       0  798.41       4  796.73      12  794.96      24  788.49      32  785.01
    75.9  763.06   131.8  735.78   143.8  729.06   159.8  718.52   163.7  717.34
   175.7  716.75   179.7  717.16   191.7  720.43   207.7  721.76   219.7  723.21
   235.6   723.2   247.6  722.26   263.6  721.63   267.6  721.65   271.6  722.31
   275.6  723.78   295.5  734.13   303.5  736.99   327.4  743.17   339.2  745.79
     367   750.1   390.7   755.8   402.6  760.57   426.4  768.72   446.2  774.49
#Mann= 3 ,-1 , 0
       0     .12       0   163.7    .045       0   179.7     .12       0
#XS Ineff= 2 , 0
                          228.59          724.83
Permanent Ineff=
       F       F
Bank Sta=163.7,179.7
XS Rating Curve= 0 ,0
Exp/Cntr=0.3,0.1

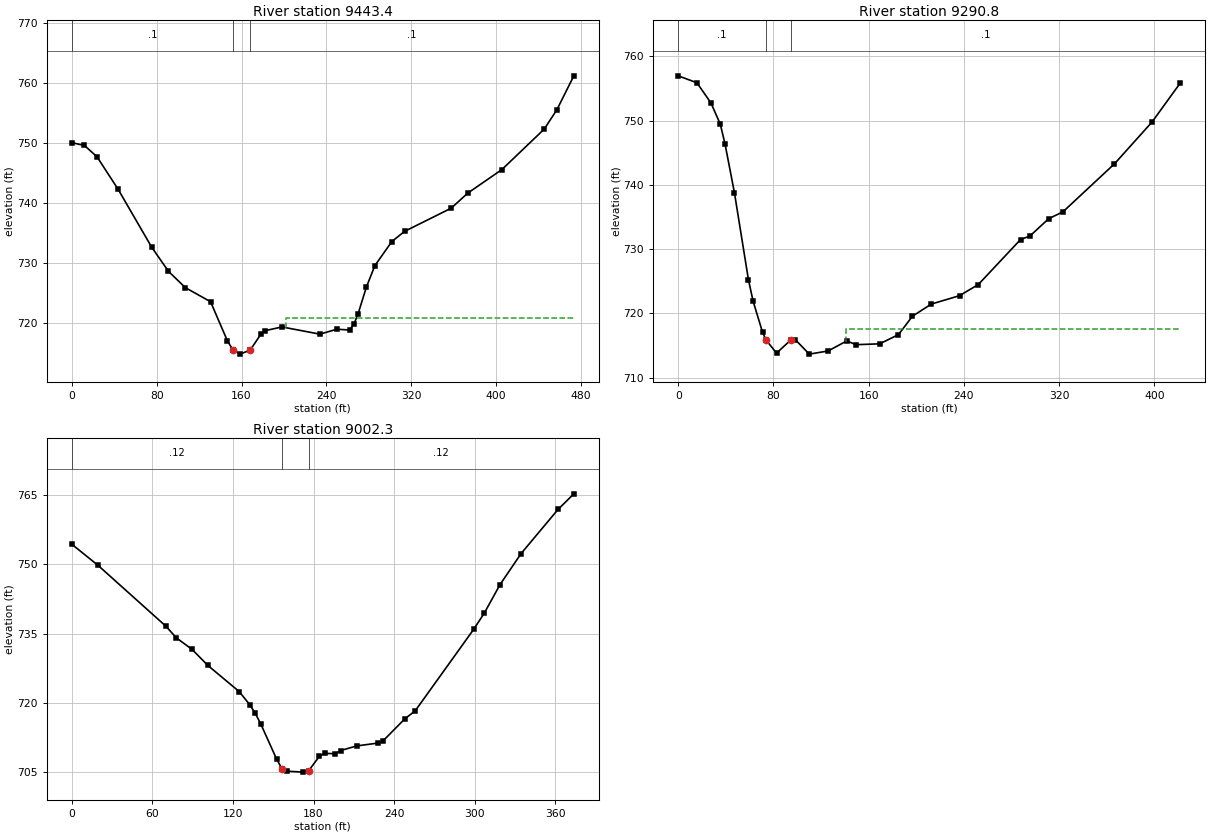
Type RM Length L Ch R = 1 ,9443.4  ,185.1,152.5,118.5
XS GIS Cut Line= 3
     2267779.329      375531.074     2267936.881      375374.824
     2267938.183      375123.522
#Sta/Elev= 30
       0  750.05    11.9  749.59    23.8   747.7    43.6  742.32    75.3  732.68
    91.1  728.67     107  725.96   130.8  723.61   146.6  717.14  151.89   715.6
   158.5   714.9  168.14  715.56   178.3  718.23   182.3   718.8   198.1  719.42
   233.9  718.22   249.8  719.04   261.8  718.91   265.8  719.83   269.8  721.58
   277.7  726.06   285.7  729.62   301.7  733.62   313.6   735.3   357.5  739.15
   373.5   741.7   405.4  745.58   445.3  752.31   457.2  755.52   473.2  761.16
#Mann= 3 , 0 , 0
       0      .1       0  151.89    .045       0  168.14      .1       0
#XS Ineff= 2 , 0
                          202.25           720.9
Permanent Ineff=
       F       F
Bank Sta=151.89,168.14
XS Rating Curve= 0 ,0
Exp/Cntr=0.3,0.1

Type RM Length L Ch R = 1 ,9290.8  ,290.1,288.5,281.7
XS GIS Cut Line= 3
     2268085.319      375529.772     2267992.871      375407.376
     2267983.756      375139.147
#Sta/Elev= 30
       0  756.95    15.7  755.87    27.5  752.73    35.4  749.39    39.3  746.36
    47.2  738.79      59  725.22    62.9  721.92    70.8  717.09   73.67   715.9
    82.6  713.84    94.4  715.85    98.3  715.94   110.1  713.68   125.9  714.17
   141.6  715.73   149.4  715.15   169.2  715.28     185  716.71   196.8  719.58
   212.6  721.46   236.3  722.77   252.1   724.5   287.6   731.5   295.5  732.05
   311.3  734.75   323.1  735.79   366.5  743.27   398.1  749.78   421.8  755.84
#Mann= 3 , 0 , 0
       0      .1       0   73.67    .045       0    94.4      .1       0
#XS Ineff= 2 , 0
                          140.55          717.62
Permanent Ineff=
       F       F
Bank Sta=73.67,94.4
XS Rating Curve= 0 ,0
Exp/Cntr=0.3,0.1

Type RM Length L Ch R = 1 ,9002.3  ,291.1,331.4,370.1
XS GIS Cut Line= 4
     2268192.104      375414.337     2268207.729      375290.639
     2268091.843      375187.774     2268068.406      375096.629
#Sta/Elev= 30
       0   754.4    19.5  749.82    70.1  736.59    77.9  734.06    89.6  731.55
   101.3  728.08   124.7  722.39   132.6  719.51   136.6  717.68   140.6  715.44
   152.5  707.74   156.5  705.66   160.4  705.11   172.4  704.91   176.3  705.19
   184.3  708.32   188.2  708.98   196.2  708.91   200.2   709.6   212.1   710.6
     228  711.22     232  711.77   247.8  716.43   255.8  718.26   299.2  735.91
   307.1  739.42   318.8  745.61   334.5  752.36     362  761.94   373.8  765.34
#Mann= 3 ,-1 , 0
       0     .12       0   156.5    .045       0   176.3     .12       0
Bank Sta=156.5,176.3
XS Rating Curve= 0 ,0
Exp/Cntr=0.3,0.1