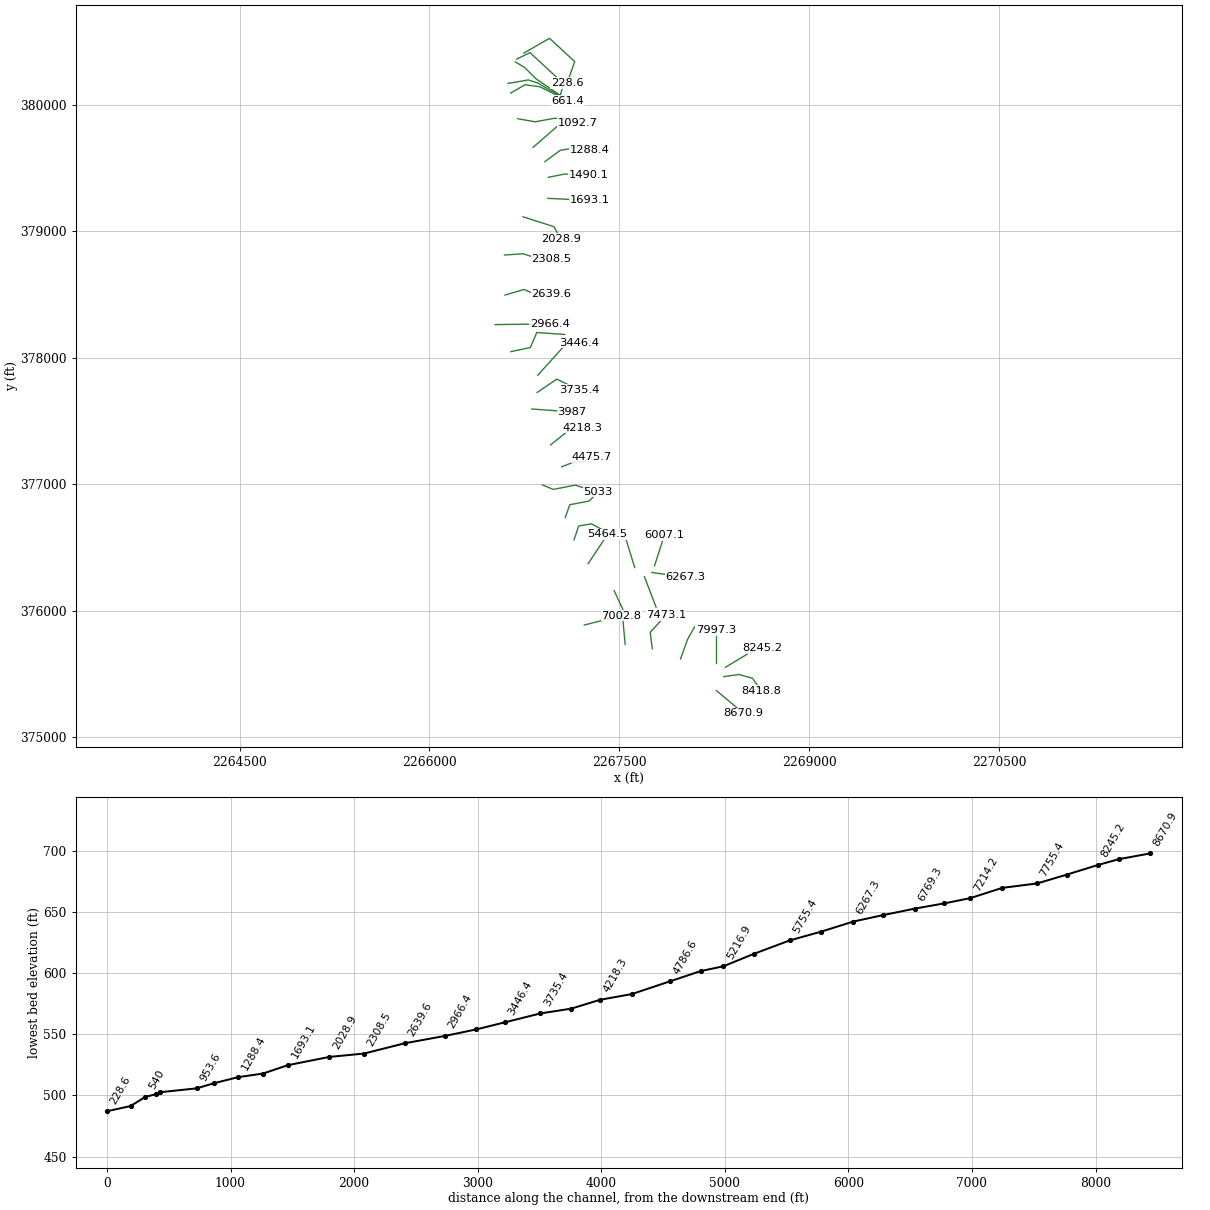
HEC-RAS study BIGRUN1.prj: BIGRUN1

--- BIGRUN1.g01 (geometry) --- (continued)

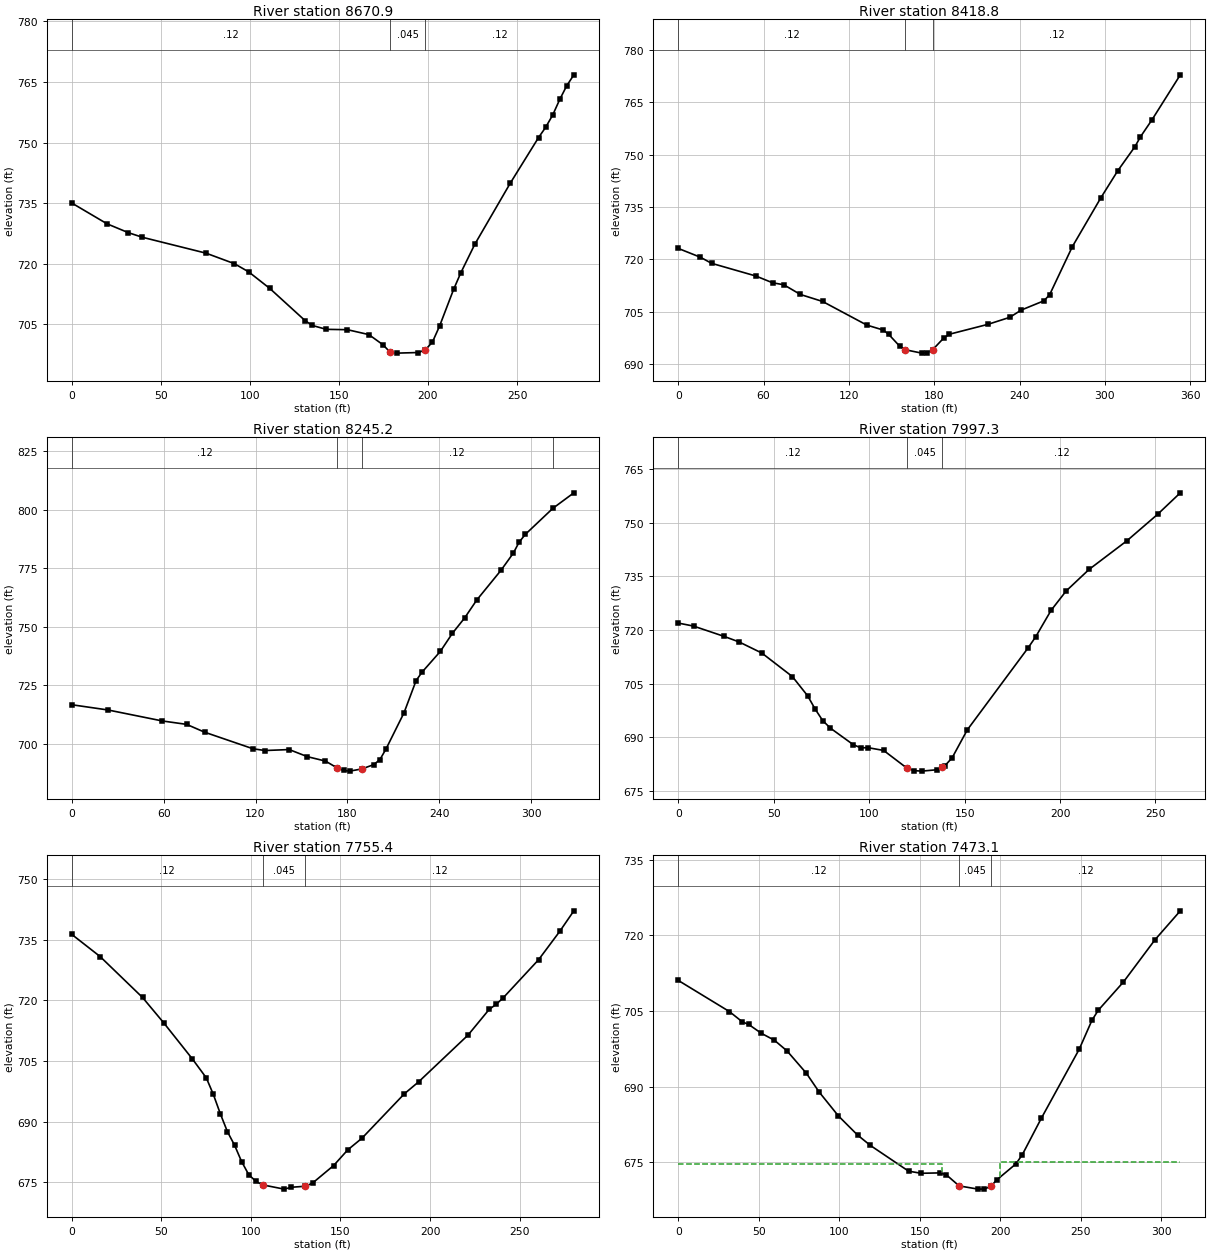
Type RM Length L Ch R = 1 ,8670.9  ,242.1,252.1,261.6
XS GIS Cut Line= 2
     2268266.322      375371.368     2268482.468      375190.379
#Sta/Elev= 30
       0  735.02    19.8  729.87    31.8  727.67    39.7  726.53    75.4   722.6
    91.3     720    99.3  717.98   111.2  713.86     131   705.9     135  704.71
   142.9  703.74   154.8  703.65   166.8  702.44   174.7  699.93   178.7  698.11
   182.6  697.85   194.6     698   198.5  698.65   202.5  700.59   206.5  704.54
   214.4  713.64   218.4  717.71   226.3  724.81   246.2  739.93   262.1  751.24
     266  753.72     270  756.78     274  760.68   277.9  764.05   281.9  766.76
#Mann= 3 ,-1 , 0
       0     .12       0   178.7    .045       0   198.5     .12       0
Bank Sta=178.7,198.5
XS Rating Curve= 0 ,0
Exp/Cntr=0.3,0.1

Type RM Length L Ch R = 1 ,8418.8  ,154.5,173.6,191.4
XS GIS Cut Line= 4
     2268324.916      375480.743     2268444.708       375497.67
     2268552.781      375467.722     2268620.489      375368.764
#Sta/Elev= 30
       0  723.14    15.6  720.61    23.4  718.88    54.6  715.24    66.3  713.31
    74.2  712.74    85.9  709.96   101.5  707.96   132.6   701.2   144.2  699.78
     148  698.53   155.8  695.12   159.6  694.15   171.2  693.18   175.1   693.3
     179  694.21   186.7  697.51   190.6  698.58   217.7  701.41   233.1  703.42
   241.1  705.49   257.1  708.15   261.1  709.87   277.1  723.65   297.1   737.6
   309.1   745.4   321.1  752.25     325  755.08     333  759.88     353   772.8
#Mann= 3 ,-1 , 0
       0     .12       0   159.6    .045       0     179     .12       0
Bank Sta=159.6,179
XS Rating Curve= 0 ,0
Exp/Cntr=0.3,0.1

Type RM Length L Ch R = 1 ,8245.2  ,223.8,247.8,271.1
XS GIS Cut Line= 3
     2268339.239      375554.962     2268531.947      375670.847
     2268628.302      375707.306
#Sta/Elev= 30
       0  716.66    23.7  714.42    59.2  709.73      75  708.28    86.8  704.93
   118.4  697.85   126.2  697.11     142  697.52   153.9  694.48   165.7   692.6
   173.4  689.65   177.5  688.59   181.5  688.31   189.4  689.24   197.2  691.08
   201.2   693.2   205.1  697.61     217  713.24   224.9  727.01   228.8  730.61
   240.7  739.43   248.6  747.18   256.6  753.75   264.5  761.39   280.3  774.06
   288.3  781.34   292.2  786.13   296.2  789.41  314.17800.5272   327.9  807.16
#Mann= 4 ,-1 , 0
       0     .12       0   173.4    .045       0   189.4     .12       0
  314.17     .06       0
Bank Sta=173.4,189.4
XS Rating Curve= 0 ,0
Exp/Cntr=0.3,0.1

Type RM Length L Ch R = 1 ,7997.3  ,249.7,242,234
XS GIS Cut Line= 2
      2268265.02       375584.91      2268265.02      375847.931
#Sta/Elev= 30
       0  721.93       8  721.09    23.9  718.23    31.9  716.65    43.8  713.55
    59.8  706.97    67.8  701.59    71.7   697.9    75.7  694.66    79.7  692.57
    91.7  687.94    95.6  687.07    99.6  687.09   107.6  686.33   119.6  681.46
   123.5  680.69   127.5  680.55   135.5  680.93   138.4681.6621   139.5  681.94
   143.5   684.3   151.4  692.07   183.3  715.02   187.3  718.14   195.3  725.48
   203.2   730.9   215.2  736.92   235.1  744.96   251.1  752.32     263  758.33
#Mann= 3 ,-1 , 0
       0     .12       0   119.6    .045       0   138.4     .12       0
Bank Sta=119.6,138.4
XS Rating Curve= 0 ,0
Exp/Cntr=0.3,0.1

Type RM Length L Ch R = 1 ,7755.4  ,291.4,282.2,273.1
XS GIS Cut Line= 3
      2267983.77      375620.066      2268039.76      375776.316
     2268097.052      375875.274
#Sta/Elev= 30
       0  736.31    15.8  730.84    39.5  720.71    51.4   714.4    67.2  705.58
    75.1  700.83      79  696.77      83  691.87    86.9  687.51    90.9  684.15
    94.8  680.13    98.8  676.88   102.8  675.22   106.7  674.34   118.6   673.3
   122.5  673.76   130.4  674.01   134.4  674.79   146.2  679.14   154.1  683.02
     162  685.89   185.7  696.89   193.6  699.82   221.2  711.39     233  717.74
     237  719.04   240.9  720.64   260.6  730.04   272.4  737.04   280.3  742.14
#Mann= 3 ,-1 , 0
       0     .12       0   106.7    .045       0   130.4     .12       0
Bank Sta=106.7,130.4
XS Rating Curve= 0 ,0
Exp/Cntr=0.3,0.1

Type RM Length L Ch R = 1 ,7473.1  ,239.4,258.9,277.4
XS GIS Cut Line= 3
     2267761.114      375700.795     2267744.187      375831.004
     2267866.583      375963.816
#Sta/Elev= 30
       0  711.04    31.8  704.86    39.8  702.83    43.8   702.3    51.7  700.54
    59.7  699.19    67.6  697.06    79.6  692.64    87.5  688.93    99.5  684.18
   111.4  680.39   119.4  678.32   143.1  673.23   150.9  672.81   162.7  672.89
   166.6  672.49   174.5  670.31   186.3  669.67   190.2  669.69   194.1  670.21
     198  671.53   209.8  674.68   213.8  676.53   225.5  683.68   249.1   697.4
     257  703.13   260.9  705.11   276.6  710.74   296.2  719.11   311.9  724.83
#Mann= 3 ,-1 , 0
       0     .12       0   174.5    .045       0   194.1     .12       0
#XS Ineff= 2 , 0
          163.62  674.66   200.1          675.02
Permanent Ineff=
       F       F
Bank Sta=174.5,194.1
XS Rating Curve= 0 ,0
Exp/Cntr=0.3,0.1

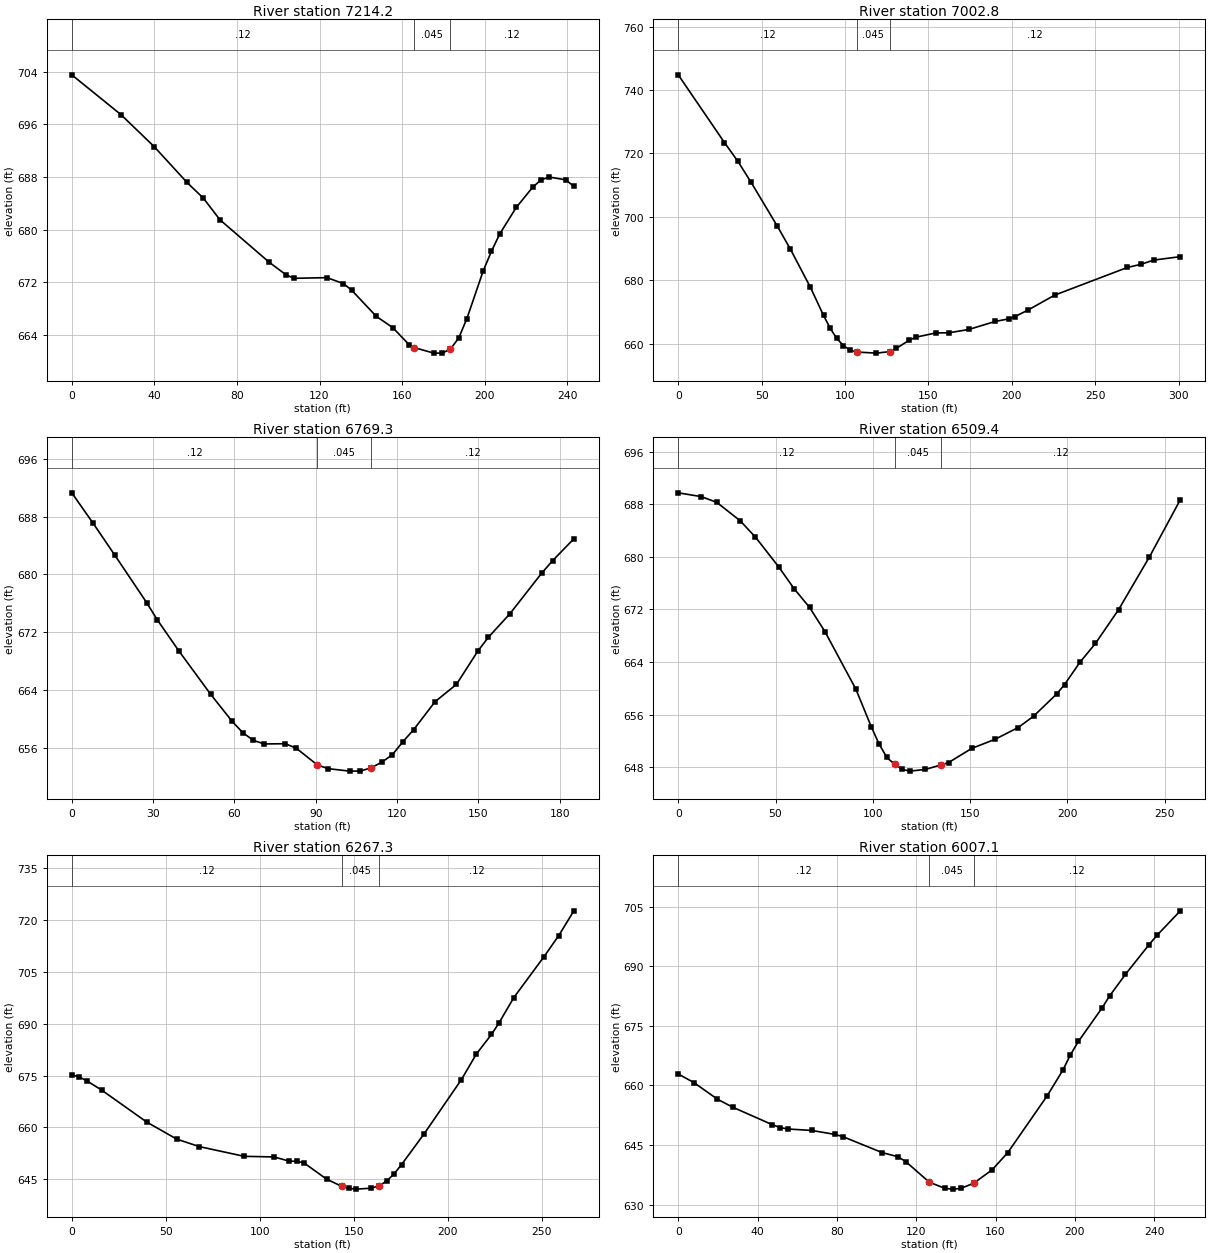
Type RM Length L Ch R = 1 ,7214.2  ,243.3,211.5,178.3
XS GIS Cut Line= 2
      2267546.27      375735.952     2267524.135      375978.139
#Sta/Elev= 30
       0   703.5    23.9  697.44    39.9  692.61    55.8  687.18    63.8  684.77
    71.8   681.5    95.7  675.05   103.7  673.18   107.6  672.63   123.6  672.73
   131.6  671.83   135.6  670.82   147.5  666.86   155.5  665.15   163.5  662.53
     166662.1069   175.4  661.28   179.4  661.28   183.4  661.88   187.4  663.56
   191.4  666.52   199.3  673.76   203.3  676.74   207.3  679.36   215.3  683.38
   223.3  686.46   227.2  687.53   231.2     688   239.2  687.57   243.2   686.6
#Mann= 3 ,-1 , 0
       0     .12       0     166    .045       0   183.4     .12       0
Bank Sta=166,183.4
XS Rating Curve= 0 ,0
Exp/Cntr=0.3,0.1

Type RM Length L Ch R = 1 ,7002.8  ,264.8,233.4,201.1
XS GIS Cut Line= 2
     2267223.354      375888.295      2267515.02      375962.514
#Sta/Elev= 30
       0  744.81    27.7  723.44    35.6  717.63    43.6  710.95    59.4  697.05
    67.3  689.73    79.2  677.79    87.1  668.88    91.1  664.82      95  661.62
      99  659.37     103  657.93   106.9  657.32   118.8  656.97   126.7  657.44
   130.7  658.45   138.6  661.09   142.6  662.01   154.4  663.34   162.4   663.4
   174.2  664.44   190.1  666.98     198  667.77     202  668.52   209.9  670.63
   225.7  675.28   269.3  684.02   277.2  684.97   285.1  686.34     301  687.42
#Mann= 3 ,-1 , 0
       0     .12       0   106.9    .045       0   126.7     .12       0
Bank Sta=106.9,126.7
XS Rating Curve= 0 ,0
Exp/Cntr=0.3,0.1

Type RM Length L Ch R = 1 ,6769.3  ,261.1,259.9,258.1
XS GIS Cut Line= 2
     2267459.031      376160.431     2267537.156      375992.462
#Sta/Elev= 30
       0  691.28     7.9  687.06    15.8   682.7    27.6  676.11    31.5  673.74
    39.4  669.47    51.2  663.43    59.1   659.7    63.1   658.1      67  657.04
      71  656.55    78.8  656.58    82.8  655.96    90.6  653.64    94.6  653.13
   102.5  652.79   106.4   652.8   110.4  653.24   114.3  654.02   118.2  655.03
   122.2  656.88   126.1  658.52     134  662.39   141.9  664.79   149.8   669.4
   153.7  671.31   161.6  674.55   173.4   680.2   177.4  681.91   185.2  684.92
#Mann= 3 ,-1 , 0
       0     .12       0    90.6    .045       0   110.4     .12       0
Bank Sta=90.6,110.4
XS Rating Curve= 0 ,0
Exp/Cntr=0.3,0.1

Type RM Length L Ch R = 1 ,6509.4  ,216.3,242.2,266
XS GIS Cut Line= 2
     2267698.614      376269.806     2267791.062       376028.92
#Sta/Elev= 30
       0  689.73    11.9  689.15    19.8  688.28    31.8  685.49    39.7  682.99
    51.6  678.48    59.5  675.17    67.5   672.3    75.4  668.63    91.3  659.87
    99.2  654.16   103.2  651.54   107.2   649.5   111.2  648.45   115.1  647.68
   119.1  647.42     127  647.68     135  648.36   138.9  648.72   150.8  650.87
   162.8  652.26   174.7  654.05   182.6  655.77   194.5  659.16   198.5  660.58
   206.4  663.96   214.4  666.83   226.3  671.98   242.1  679.97     258  688.68
#Mann= 3 ,-1 , 0
       0     .12       0   111.2    .045       0     135     .12       0
Bank Sta=111.2,135
XS Rating Curve= 0 ,0
Exp/Cntr=0.3,0.1

Type RM Length L Ch R = 1 ,6267.3  ,228.1,260.2,291.6
XS GIS Cut Line= 2
     2267757.208       376303.66     2268021.531      376265.899
#Sta/Elev= 30
       0  675.28       4  674.57       8  673.49    15.9   670.8    39.8  661.57
    55.8  656.61    67.8  654.44    91.7  651.62   107.6  651.44   115.6  650.23
   119.6  650.18   123.5  649.71   135.5  645.02   143.5  642.94   147.4  642.33
   151.4  642.12   159.2  642.39   163.4  643.06   167.4  644.43   171.4  646.54
   175.4  649.25   187.3  658.07   207.2  673.84   215.2  681.28   223.2  686.92
   227.2  690.26   235.1  697.61   251.1  709.42     259  715.57     267  722.72
#Mann= 3 ,-1 , 0
       0     .12       0   143.5    .045       0   163.4     .12       0
Bank Sta=143.5,163.4
XS Rating Curve= 0 ,0
Exp/Cntr=0.3,0.1

Type RM Length L Ch R = 1 ,6007.1  ,237.6,251.7,264.3
XS GIS Cut Line= 2
     2267778.041      376355.743     2267856.166      376596.629
#Sta/Elev= 30
       0  662.85     7.9  660.69    19.8  656.49    27.7  654.44    47.5  650.08
    51.4  649.36    55.4     649    67.3  648.64    79.1  647.64    83.1  647.07
   102.9  643.05   110.8  642.03   114.8  640.78   126.6  635.62   134.5  634.06
   138.5  633.87   142.4  634.03     149 635.356   158.3  638.73   166.2  643.07
     186  657.31   193.9  663.75   197.8  667.69   201.8  671.04   213.7  679.45
   217.6  682.54   225.5  687.91   237.4  695.38   241.4  697.73   253.2  703.92
#Mann= 3 ,-1 , 0
       0     .12       0   126.6    .045       0     149     .12       0
Bank Sta=126.6,149
XS Rating Curve= 0 ,0
Exp/Cntr=0.3,0.1

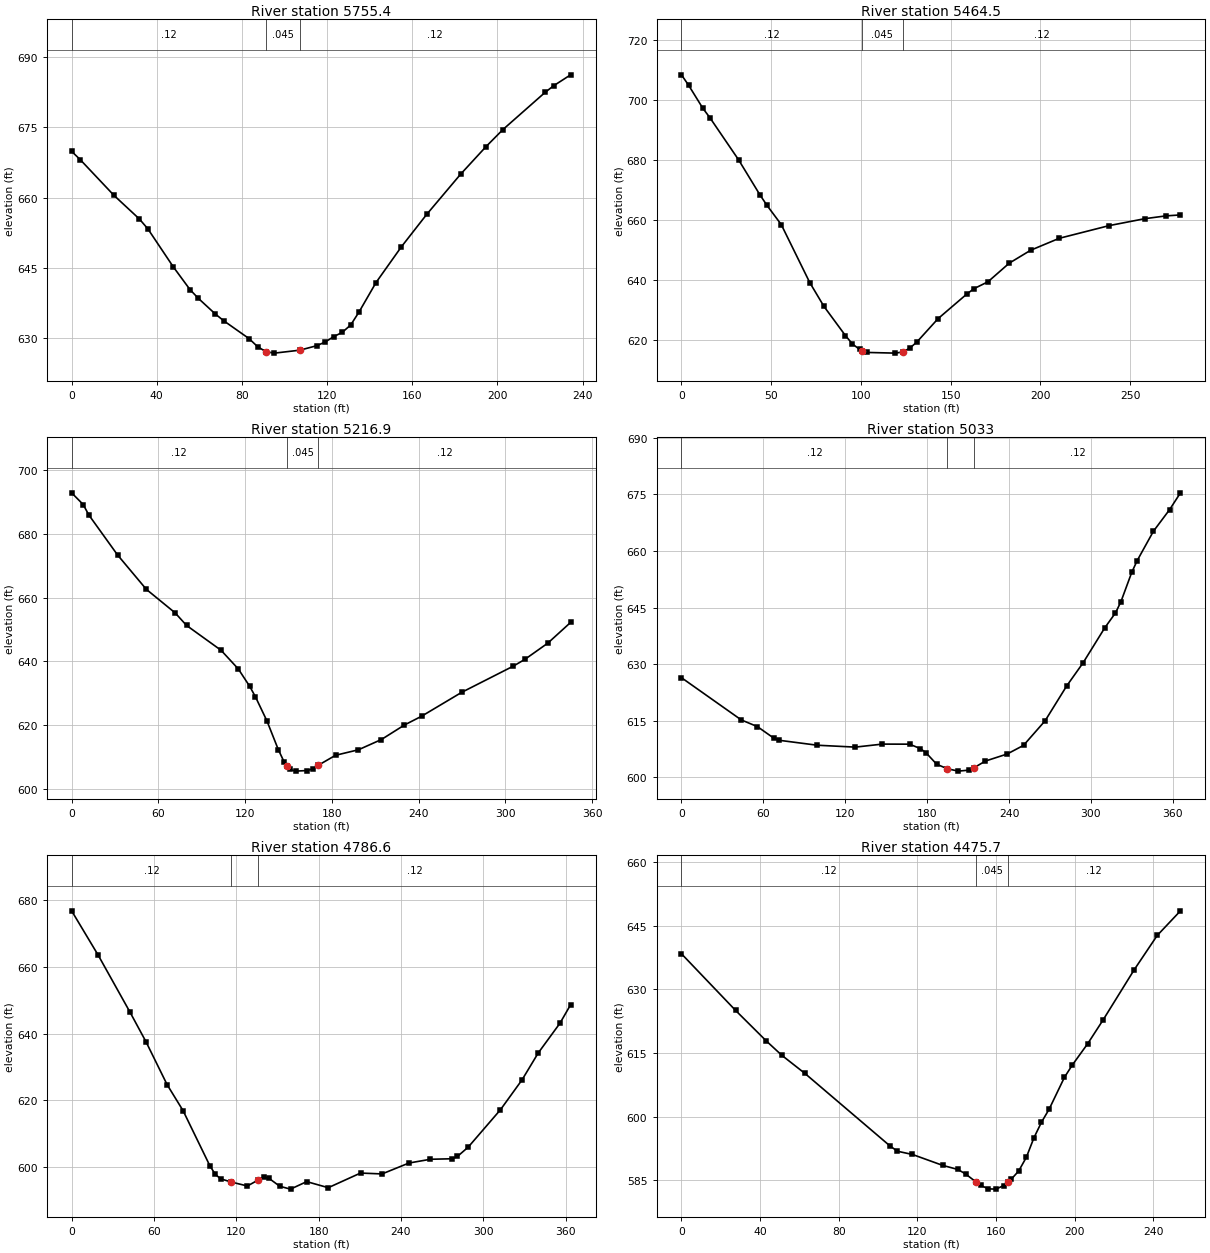
Type RM Length L Ch R = 1 ,5755.4  ,310.2,290.9,271.2
XS GIS Cut Line= 2
     2267621.791      376342.722     2267552.781      376566.681
#Sta/Elev= 30
       0  669.85       4   668.1    19.9  660.45    31.8  655.43    35.8  653.32
    47.7  645.24    55.6  640.35    59.6  638.45    67.5  635.14    71.5  633.68
    83.4  629.87    87.4  628.15    91.4  627.07    95.3  626.79   107.2  627.42
   115.2  628.38   119.2  629.18   123.1  630.31   127.1  631.21   131.1   632.8
     135  635.56     143  641.86   154.9  649.48   166.8   656.4   182.7  664.96
   194.6  670.83   202.6   674.5   222.4  682.43   226.4  683.84   234.4  686.18
#Mann= 3 ,-1 , 0
       0     .12       0    91.4    .045       0   107.2     .12       0
Bank Sta=91.4,107.2
XS Rating Curve= 0 ,0
Exp/Cntr=0.3,0.1

Type RM Length L Ch R = 1 ,5464.5  ,266,247.6,228.9
XS GIS Cut Line= 2
     2267254.604      376373.972     2267408.249      376605.743
#Sta/Elev= 30
       0  708.47       4  704.98    11.9  697.35    15.9  694.15    31.8   680.2
    43.7  668.53    47.7  664.96    55.6  658.62    71.5  639.29    79.4  631.36
    91.4  621.62    95.3  618.83    99.3  617.02   100.8  616.64   103.3  616.02
   119.2  615.79   123.2  616.15   127.1  617.39   131.1  619.43     143  627.27
   158.9   635.4   162.9  637.22   170.8  639.54   182.7  645.76   194.6  650.05
   210.5  654.02   238.4  658.26   258.2  660.56   270.1   661.5   278.1  661.81
#Mann= 3 ,-1 , 0
       0     .12       0   100.8    .045       0   123.2     .12       0
Bank Sta=100.8,123.2
XS Rating Curve= 0 ,0
Exp/Cntr=0.3,0.1

Type RM Length L Ch R = 1 ,5216.9  ,182.7,183.9,183.7
XS GIS Cut Line= 4
     2267142.624      376561.472     2267179.083      376670.847
     2267280.645      376687.774     2267392.624      376627.879
#Sta/Elev= 30
       0  692.84       8  689.18    11.9   685.9    31.8  673.35    51.7  662.58
    71.6  655.21    79.5  651.27   103.4  643.47   115.3  637.63   123.2  632.17
   127.2  628.86   135.1  621.35     143  612.32     147  608.48  148.91607.3291
   150.9  606.13   154.9  605.59   162.8  605.77   166.8  606.28   170.7  607.45
   182.6  610.56   198.4  612.28   214.3   615.5   230.2  620.04   242.1   622.8
   269.8  630.28   305.6  638.52   313.5  640.61   329.4  645.71   345.2  652.21
#Mann= 3 ,-1 , 0
       0     .12       0  148.91    .045       0   170.7     .12       0
Bank Sta=148.91,170.7
XS Rating Curve= 0 ,0
Exp/Cntr=0.3,0.1

Type RM Length L Ch R = 1 ,5033    ,244.9,246.4,244.6
XS GIS Cut Line= 4
     2267073.614      376737.254      2267108.77      376838.816
     2267261.114      376867.462     2267334.031      376940.379
#Sta/Elev= 30
       0  626.41    43.8  615.23    55.7  613.44    67.7  610.38    71.6  609.83
    99.5  608.52   127.4  608.02   147.2  608.82   167.1   608.8     175  607.63
     179  606.59     187  603.48   194.9  602.28   202.9  601.66   210.8  601.93
   214.6 602.614   222.7  604.33   238.6  606.19   250.6  608.48   266.4  614.98
   282.3  624.26   294.2  630.32   310.1   639.6     318  643.58     322  646.56
   329.9  654.31   333.9  657.44   345.8  665.21   357.7  670.96   365.6  675.38
#Mann= 3 ,-1 , 0
       0     .12       0   194.9    .045       0   214.6     .12       0
Bank Sta=194.9,214.6
XS Rating Curve= 0 ,0
Exp/Cntr=0.3,0.1

Type RM Length L Ch R = 1 ,4786.6  ,312.3,310.9,305.1
XS GIS Cut Line= 4
     2266892.624      376995.066     2266978.562       376959.91
     2267151.739      376993.764     2267241.583      376965.118
#Sta/Elev= 30
       0  676.84    19.3  663.58    42.6   646.4    54.2  637.56    69.6  624.68
    81.2   616.9   100.7  600.39   104.6  597.84   108.5  596.45   116.4  595.47
   128.1  594.29     136  596.11   139.9  596.93   143.8  596.59   151.7   594.2
   159.5  593.35   171.3   595.6     187  593.78   210.5  598.17   226.2  597.91
   245.8  601.18   261.5  602.31   277.2  602.46   281.1  603.15     289  605.96
   312.5  617.18   328.2  626.13     340   634.2   355.8   643.1   363.6  648.68
#Mann= 3 ,-1 , 0
       0     .12       0   116.4    .045       0     136     .12       0
Bank Sta=116.4,136
XS Rating Curve= 0 ,0
Exp/Cntr=0.3,0.1

Type RM Length L Ch R = 1 ,4475.7  ,243.1,257.4,270.8
XS GIS Cut Line= 4
     2267044.968      377138.295     2267136.114      377174.754
     2267228.562      377181.264     2267283.249      377212.514
#Sta/Elev= 30
       0  638.42    27.5  625.06    43.2  617.82      51  614.47    62.8  610.17
   105.9  593.12   109.8  591.81   117.5  591.04   132.9  588.46   140.6   587.5
   144.5  586.44   149.8 584.561   152.2  583.75   156.1  582.92     160  582.86
   163.8  583.69  165.89584.4875   167.7  585.18   171.5  587.13   175.4  590.36
   179.3  595.01   183.1  598.65     187  601.73   194.8  609.26   198.7   612.1
   206.6  617.18   214.5  622.84   230.2   634.6     242  642.76   253.8  648.56
#Mann= 3 ,-1 , 0
       0     .12       0   149.8    .045       0  165.89     .12       0
Bank Sta=149.8,165.89
XS Rating Curve= 0 ,0
Exp/Cntr=0.3,0.1

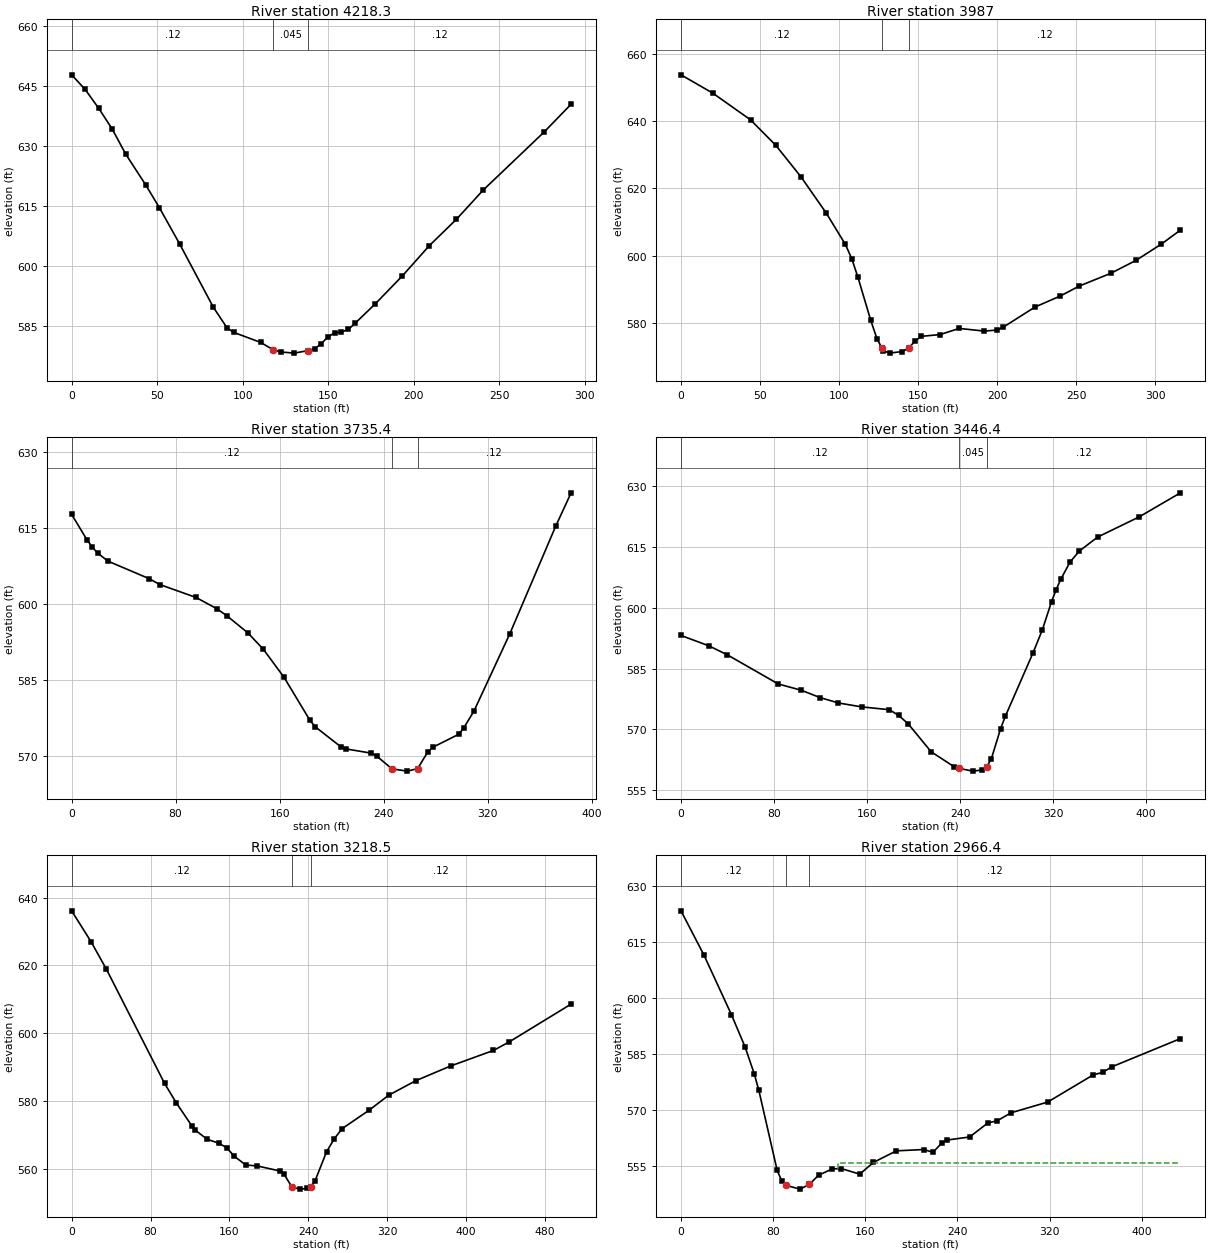
Type RM Length L Ch R = 1 ,4218.3  ,248.3,231.4,213.5
XS GIS Cut Line= 3
     2266957.729      377311.472     2267086.635      377415.639
     2267209.031      377446.889
#Sta/Elev= 30
       0  647.82     7.9  644.17    15.8  639.46    23.7  634.28    31.6     628
    43.4  620.22    51.3  614.59    63.1  605.56    82.9  589.65    90.8  584.56
    94.7  583.39   110.5  580.88     118 578.996   122.3  578.48   130.2  578.19
   138.1  578.81   142.1  579.31     146  580.55     150  582.31   153.9  583.28
   157.8  583.48   161.8  584.12   165.7  585.62   177.6  590.53   193.4   597.5
   209.2  605.09     225  611.66   240.7  618.99   276.3   633.5   292.1  640.47
#Mann= 3 ,-1 , 0
       0     .12       0     118    .045       0   138.1     .12       0
Bank Sta=118,138.1
XS Rating Curve= 0 ,0
Exp/Cntr=0.3,0.1

Type RM Length L Ch R = 1 ,3987    ,259.7,251.6,242.5
XS GIS Cut Line= 2
     2266809.291      377595.327     2267124.395      377571.889
#Sta/Elev= 30
       0  653.75      20  648.34      44  640.37      60  632.78      76  623.37
      92  612.57     104  603.33     108  599.13     112  593.49     120  580.83
     124  575.26   127.1572.5076     128  571.71     132  570.99     140  571.47
     144  572.46     148  574.54     152  575.98     164  576.51     176  578.34
     192  577.54     200  577.86     204  578.74     224   584.7     240  587.98
     252  590.94     272  594.74     288   598.6     304  603.44     316  607.58
#Mann= 3 ,-1 , 0
       0     .12       0   127.1    .045       0     144     .12       0
Bank Sta=127.1,144
XS Rating Curve= 0 ,0
Exp/Cntr=0.3,0.1

Type RM Length L Ch R = 1 ,3735.4  ,258.9,289,317.3
XS GIS Cut Line= 3
     2266850.958      377725.535     2267005.906      377831.004
     2267182.989      377745.066
#Sta/Elev= 30
       0  617.67      12  612.56      16  611.19    19.9  610.06    27.9  608.45
    59.8  604.97    67.8  603.83    95.7  601.28   111.7  599.06   119.6  597.63
   135.6  594.29   147.6  591.03   163.5   585.5   183.4  577.02   187.4  575.77
   207.1  571.83   211.1   571.4   230.7  570.56   234.7     570   246.5  567.46
   258.3  567.02   266.2  567.51     274   570.8     278  571.74   297.7  574.27
   301.6   575.5   309.5  578.84     337  594.03   372.5  615.37   384.3  621.92
#Mann= 3 ,-1 , 0
       0     .12       0   246.5    .045       0   266.2     .12       0
Bank Sta=246.5,266.2
XS Rating Curve= 0 ,0
Exp/Cntr=0.3,0.1

Type RM Length L Ch R = 1 ,3446.4  ,219.5,227.9,234.5
XS GIS Cut Line= 3
     2266856.166      377862.254     2267064.499      378092.722
     2267180.385      378118.764
#Sta/Elev= 30
       0  593.17    23.9  590.62    39.8   588.4    83.6  581.21   103.6  579.64
   119.5  577.86   135.4  576.52   155.3  575.56   179.2  574.86   187.2  573.44
   195.2  571.42   215.1  564.49     235  560.77     239   560.4   250.9  559.72
   258.9     560   262.9  560.76   266.9  562.82   274.8  570.21   278.8   573.2
   302.7   588.9   310.7  594.58   318.6  601.51   322.6  604.49   326.5     607
   334.4  611.22   342.4  613.96   358.2  617.42   393.8  622.38   429.4  628.33
#Mann= 3 ,-1 , 0
       0     .12       0     239    .045       0   262.9     .12       0
Bank Sta=239,262.9
XS Rating Curve= 0 ,0
Exp/Cntr=0.3,0.1

Type RM Length L Ch R = 1 ,3218.5  ,277.5,252.2,224.9
XS GIS Cut Line= 4
     2266643.927      378048.452     2266797.572      378081.004
     2266848.354      378199.493     2267068.406      378183.868
#Sta/Elev= 30
       0   636.1    19.6  627.04    35.3  618.85    94.2  585.22     106  579.52
   121.7  572.76   125.6  571.35   137.4  568.72   149.2  567.55   157.1  566.26
   164.9  563.72   176.6  561.11   188.3  560.84   211.8  559.32   215.6  558.32
   223.5  554.62   231.3     554   239.1   554.2     243  554.71   246.9  556.45
   258.6  565.05   266.4  568.85   274.2  571.81   301.7  577.27   321.4  581.67
     349  585.98   384.4  590.33   427.8  594.91   443.5  597.37   506.6  608.59
#Mann= 3 ,-1 , 0
       0     .12       0   223.5    .045       0     243     .12       0
Bank Sta=223.5,243
XS Rating Curve= 0 ,0
Exp/Cntr=0.3,0.1

Type RM Length L Ch R = 1 ,2966.4  ,333.6,326.8,318
XS GIS Cut Line= 2
     2266518.927      378261.993      2266952.52      378267.202
#Sta/Elev= 30
       0  623.26    19.9  611.44    43.8  595.44    55.7  586.75    63.6   579.6
    67.6  575.16    83.5  553.72    87.5  550.89    91.5  549.68   103.4   548.7
   111.4  549.97   119.4  552.41   131.3  554.12   139.2   554.2   155.2  552.72
   167.1  555.86     187  558.96   210.8  559.31   218.8  558.57   226.8  561.18
   230.7  561.84   250.6  562.67   266.5  566.45   274.5     567   286.4  569.14
   318.3  572.02     358  579.33     366  579.96     374  581.46   433.6  589.03
#Mann= 3 ,-1 , 0
       0     .12       0    91.5    .045       0   111.4     .12       0
#XS Ineff= 2 , 0
                          136.22          555.66
Permanent Ineff=
       F       F
Bank Sta=91.5,111.4
XS Rating Curve= 0 ,0
Exp/Cntr=0.3,0.1

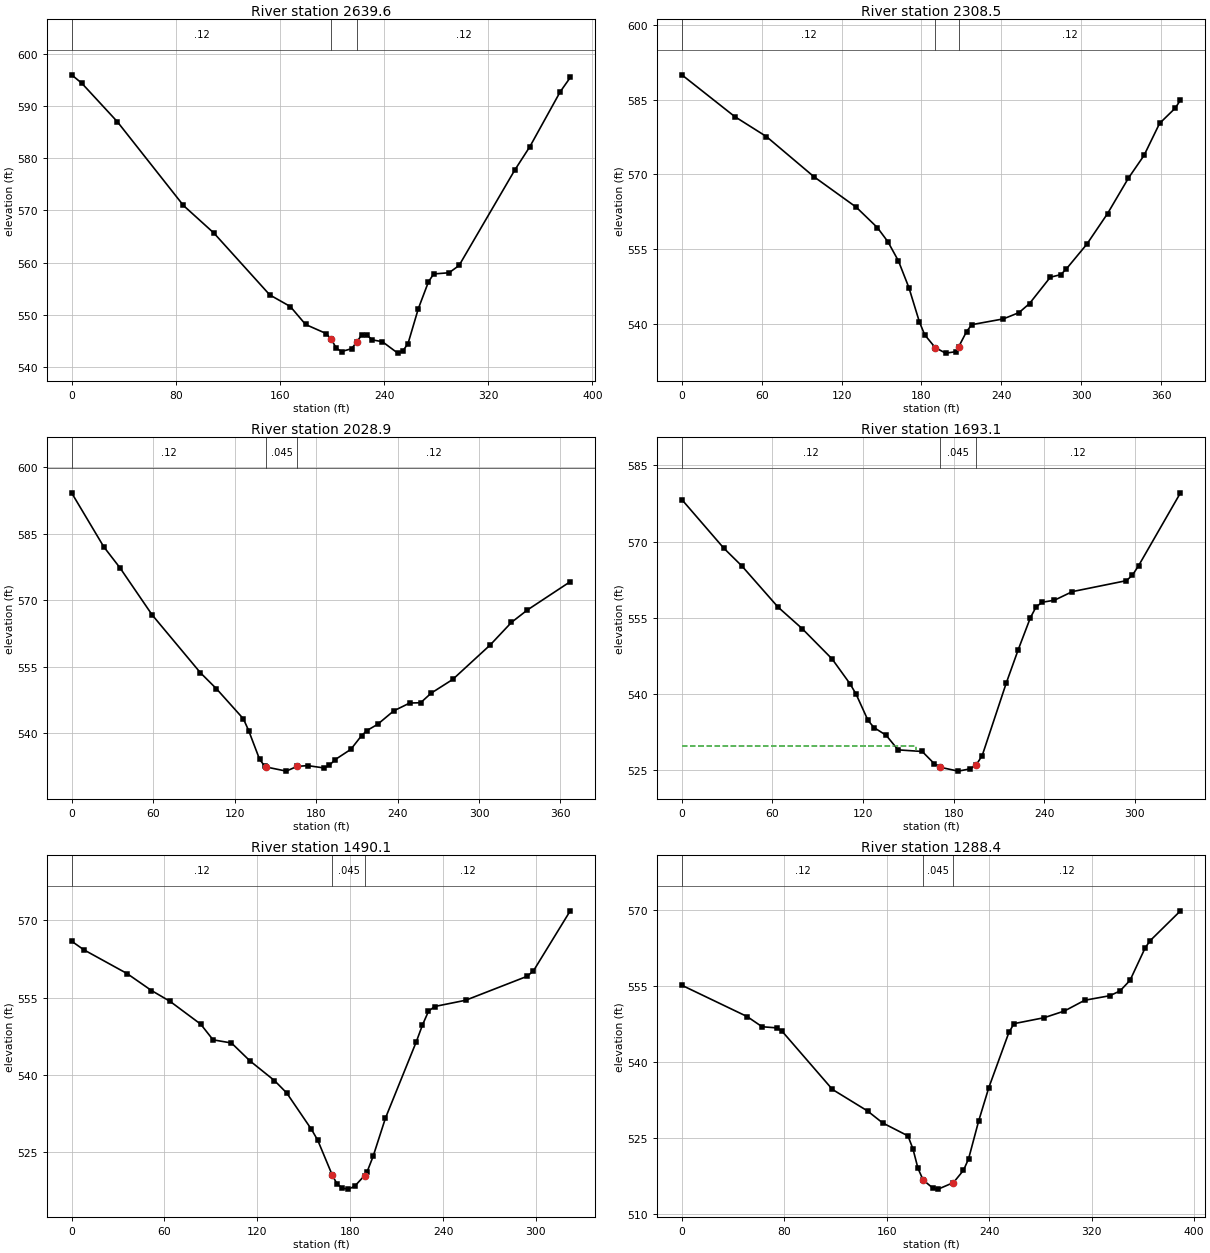
Type RM Length L Ch R = 1 ,2639.6  ,326.9,331,331.9
XS GIS Cut Line= 4
     2266597.052      378495.066     2266746.791      378539.337
     2266870.489      378488.556     2266962.937      378500.274
#Sta/Elev= 30
       0  595.97     7.8  594.37    35.1     587    85.9  570.95   109.3  565.67
   152.2  553.83     168   551.6   179.7  548.17   195.5  546.43   199.4  545.35
   203.3  543.64   207.3  542.98   215.1  543.53   219.1  544.87     223  546.22
   226.9  546.12   230.9  545.22   238.7  544.87   250.5  542.68   254.5  543.13
   258.4  544.52   266.3  551.19   274.1  556.34   278.1  557.84   289.9  558.07
   297.6  559.46   340.3   577.7     352  582.23   375.3  592.73     383  595.46
#Mann= 3 ,-1 , 0
       0     .12       0   199.4    .045       0   219.1     .12       0
Bank Sta=199.4,219.1
XS Rating Curve= 0 ,0
Exp/Cntr=0.3,0.1

Type RM Length L Ch R = 1 ,2308.5  ,279.5,279.6,279.6
XS GIS Cut Line= 4
     2266593.145      378811.472     2266739.742       378821.51
      2266852.26      378785.431     2266961.635      378781.524
#Sta/Elev= 30
       0  589.94    39.7  581.59    63.5  577.59    99.3  569.53     131  563.45
   146.9  559.36   154.8  556.53   162.7   552.7   170.6  547.33   178.4  540.54
   182.4  537.92   190.3  535.35   198.1  534.23   205.8  534.51  208.01 535.515
   213.9  538.54   217.8  539.93   241.5  541.08   253.3  542.34   261.2  544.16
   276.8  549.42   284.6  549.94   288.6     551   304.2  556.02   319.8  562.16
   335.5  569.27   347.2   573.8   358.9  580.22   370.6  583.26   374.6  584.89
#Mann= 3 ,-1 , 0
       0     .12       0   190.3    .045       0  208.01     .12       0
Bank Sta=190.3,208.01
XS Rating Curve= 0 ,0
Exp/Cntr=0.3,0.1

Type RM Length L Ch R = 1 ,2028.9  ,328.2,335.8,340.4
XS GIS Cut Line= 3
     2266739.413      379113.556     2266984.204      379035.431
     2267036.288      378938.208
#Sta/Elev= 30
       0  594.18    23.7  582.02    35.6   577.3    59.3  566.69    94.9  553.64
   106.7  550.04   126.5  543.28   130.4  540.62   138.4  534.18   142.3  532.57
   143.4532.4215   158.1   531.5     166  532.57   173.9  532.74   185.8  532.22
   189.8  532.77   193.7  534.02   205.6   536.4   213.5  539.48   217.4  540.63
   225.3  542.03   237.2  545.07     249  546.84     257   546.9   264.8  549.07
   280.6  552.14   308.2   559.9   323.9     565   335.7  567.81   367.2  574.17
#Mann= 3 ,-1 , 0
       0     .12       0   143.4    .045       0     166     .12       0
Bank Sta=143.4,166
XS Rating Curve= 0 ,0
Exp/Cntr=0.3,0.1

Type RM Length L Ch R = 1 ,1693.1  ,201.7,203,202.6
XS GIS Cut Line= 2
     2266935.593      379259.389     2267265.454      379243.764
#Sta/Elev= 30
       0  578.27    27.8  568.69    39.8  565.17    63.7  557.08    79.6  552.86
    99.5  546.86   111.4  541.95   115.4  539.92   123.3  534.74   127.3  533.32
   135.3  531.82   143.2  528.94   159.2  528.62   167.1  526.23   171.1  525.51
     183  524.75     191   525.2   194.9  525.98   198.9  527.81   214.8  542.08
   222.8  548.72   230.8  554.98   234.7  557.17   238.7  558.04   246.7  558.43
   258.6  560.13   294.4  562.29   298.4  563.38   302.4  565.21   330.2   579.6
#Mann= 3 ,-1 , 0
       0     .12       0   171.1    .045       0   194.9     .12       0
#XS Ineff= 2 , 0
          155.31  529.73
Permanent Ineff=
       F       F
Bank Sta=171.1,194.9
XS Rating Curve= 0 ,0
Exp/Cntr=0.3,0.1

Type RM Length L Ch R = 1 ,1490.1  ,196.7,201.7,206.6
XS GIS Cut Line= 3
     2266940.368      379425.622      2267068.84      379451.663
     2267259.812      379442.983
#Sta/Elev= 30
       0  565.92     7.9  564.25    35.8  559.65    51.6  556.36    63.6  554.26
    83.4  549.84    91.4   546.8   103.3  546.19   115.2  542.73   131.1   538.9
     139   536.5     155  529.44     159  527.37  168.49520.5401   171.4  518.94
   174.9  518.05   178.9  517.87   182.9  518.43   189.3520.5075   190.8  521.13
   194.8   524.2   202.8  531.64   222.7  546.41   226.7  549.67   230.6  552.34
   234.6  553.26   254.6  554.47   294.4  559.12   298.4  560.16   322.2   571.8
#Mann= 3 ,-1 , 0
       0     .12       0  168.49    .045       0   189.3     .12       0
Bank Sta=168.49,189.3
XS Rating Curve= 0 ,0
Exp/Cntr=0.3,0.1

Type RM Length L Ch R = 1 ,1288.4  ,184.1,195.7,207.1
XS GIS Cut Line= 4
     2266912.156       379549.32     2267031.947      379637.861
     2267179.517      379663.903     2267266.322      379637.861
#Sta/Elev= 30
       0  555.17      51  548.99    62.7  546.98    74.5  546.75    78.4  546.06
   117.6  534.61     145  530.36   156.8     528   176.6  525.44   180.5  522.86
   184.4  519.04   188.4  516.75   196.3  515.07   200.2  514.93   212.1  516.22
   219.9  518.63   223.9  520.89   231.8  528.38   239.7  534.95   255.4  545.85
   259.4  547.59     283  548.77   298.8  550.09   314.6  552.21   334.3  553.11
   342.2  554.05     350  556.14   361.9  562.59   365.8  563.99   389.4  569.86
#Mann= 3 ,-1 , 0
       0     .12       0   188.4    .045       0   212.1     .12       0
Bank Sta=188.4,212.1
XS Rating Curve= 0 ,0
Exp/Cntr=0.3,0.1

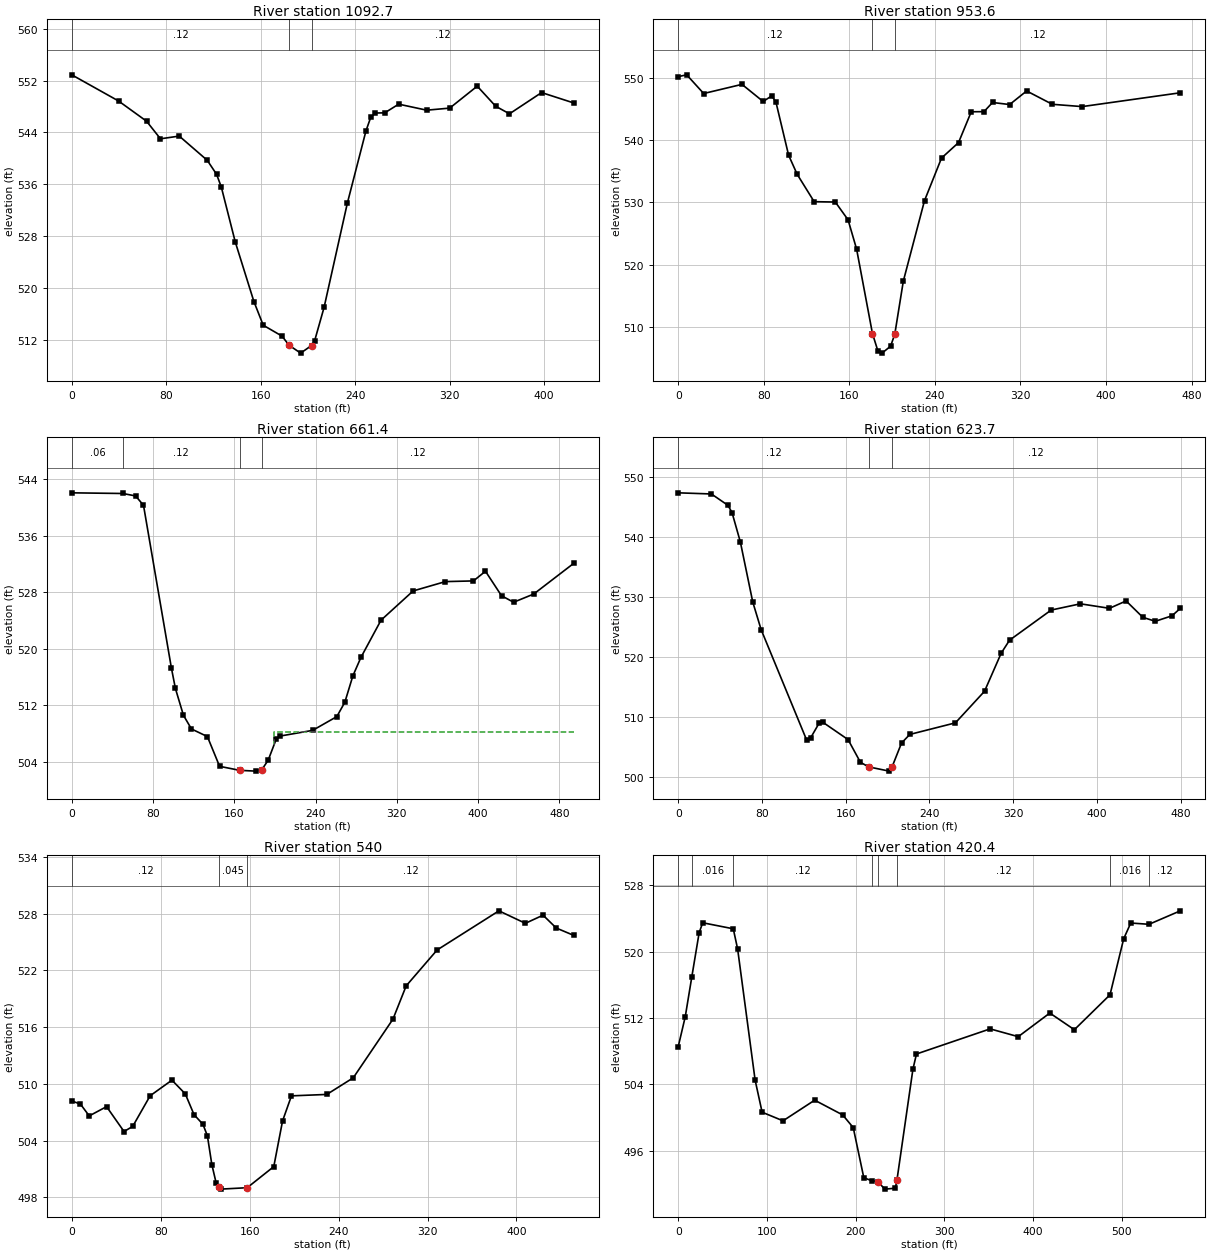
Type RM Length L Ch R = 1 ,1092.7  ,149.8,139.1,126.7
XS GIS Cut Line= 3
     2266819.274      379662.601     2267043.232      379857.045
     2267171.704      379857.045
#Sta/Elev= 30
       0   552.9    39.6  548.86    63.3  545.74    75.1  543.02      91  543.44
   114.7   539.7   122.6  537.54   126.6  535.58   138.4  527.11   154.2  517.89
   162.1  514.23     178  512.55  183.99511.1371   193.8  509.92     203511.0969
   205.6  511.81   213.6  516.97   233.3  533.06   249.1  544.25   253.1  546.32
     257     547     265  547.03   276.8  548.37   300.5  547.44     320  547.76
   343.3  551.15   358.9  548.05   370.6  546.88   397.8  550.16   425.1  548.55
#Mann= 3 ,-1 , 0
       0     .12       0  183.99    .045       0     203     .12       0
Bank Sta=183.99,203
XS Rating Curve= 0 ,0
Exp/Cntr=0.3,0.1

Type RM Length L Ch R = 1 ,953.6   ,298.2,292.2,284.3
XS GIS Cut Line= 4
     2266698.614      379888.295     2266835.467      379864.129
     2266983.915      379891.412     2267163.458      379889.597
#Sta/Elev= 30
       0  550.16     7.9  550.45    23.8  547.45    59.6  548.92    79.4  546.17
    87.4  547.07    91.3  546.12   103.2  537.55   111.2  534.49   127.1  530.09
   146.9  530.03   158.8  527.18   166.8  522.47  181.61508.9248   186.6  506.19
   190.6  505.78   198.6   506.9   202.5  508.82   210.5  517.35   230.3  530.26
   246.2  537.09   262.1  539.57     274  544.52   285.9  544.54   293.9  546.01
   309.9  545.68   325.8  547.86   349.8  545.72   377.7  545.35   469.5  547.57
#Mann= 3 ,-1 , 0
       0     .12       0  181.61    .045       0   202.5     .12       0
Bank Sta=181.61,202.5
XS Rating Curve= 0 ,0
Exp/Cntr=0.3,0.1

Type RM Length L Ch R = 1 ,661.4   ,41.4,37.6,33.5
XS GIS Cut Line= 4
     2266642.624       380091.42     2266754.604      380156.524
     2266873.093      380140.899     2267091.843      380030.222
#Sta/Elev= 30
       0  542.07   50.35 541.975    62.8  541.63    70.6  540.31    98.1  517.24
     102  514.38   109.9  510.58   117.8  508.64   133.5  507.56   145.5  503.35
   165.4  502.78   181.3  502.67   187.1502.8835   193.3  504.21   201.2  507.18
   205.2  507.64   237.1  508.44   260.9  510.39   268.8  512.43   276.7  516.16
   284.6  518.76   304.4  524.04     336  528.18   367.7   529.5   395.4   529.6
   407.2  530.97     423   527.5   434.9  526.58   454.7  527.74   494.2   532.1
#Mann= 4 ,-1 , 0
       0     .06       0   50.35     .12       0   165.4    .045       0
   187.1     .12       0
#XS Ineff= 2 , 0
                          199.17          508.28
Permanent Ineff=
       F       F
Bank Sta=165.4,187.1
XS Rating Curve= 0 ,0
Exp/Cntr=0.3,0.1

Type RM Length L Ch R = 1 ,623.7   ,93.7,83.8,37.9
XS GIS Cut Line= 4
      2266621.27      380167.202     2266781.166      380194.806
     2266856.166      380170.847     2267062.416      380050.535
#Sta/Elev= 30
       0   547.3    31.7  547.11    47.5  545.22    51.4  544.02    59.4  539.09
    71.2  529.13    79.2  524.53   122.7  506.14   126.6  506.52   134.6  508.94
   138.5  509.06   162.3  506.21   174.1  502.43   181.9  501.67   201.6  500.96
  204.32501.6536   213.4  505.64   221.3  507.07   264.9     509   292.7  514.26
   308.6  520.59   316.6  522.76   356.4  527.78   384.3  528.82   412.1  528.07
     428   529.3     444  526.57   455.9  525.91   471.8  526.82   479.8  528.06
#Mann= 3 ,-1 , 0
       0     .12       0   181.9    .045       0  204.32     .12       0
Bank Sta=181.9,204.32
XS Rating Curve= 0 ,0
Exp/Cntr=0.3,0.1

Type RM Length L Ch R = 1 ,540     ,119.1,119.6,144.6
XS GIS Cut Line= 4
     2266679.343       380337.34     2266753.041      380292.722
      2266840.02      380205.222      2267040.02      380068.764
#Sta/Elev= 30
       0  508.19     7.8  507.86    15.7  506.61    31.3  507.59      47  504.96
    54.8   505.5    70.5  508.74    90.1  510.39   102.1  508.94     110  506.74
     118  505.72     122   504.5     126  501.46   129.9   499.5  132.69499.0606
   133.9  498.87   157.8  499.02   181.7  501.25   189.6  506.08   197.6  508.73
   229.4  508.88   253.2  510.64   288.9  516.84   300.8  520.36   328.6  524.15
   384.2  528.29     408  526.97   423.9  527.83   435.8  526.47   451.6  525.69
#Mann= 3 ,-1 , 0
       0     .12       0  132.69    .045       0   157.8     .12       0
Bank Sta=132.69,157.8
XS Rating Curve= 0 ,0
Exp/Cntr=0.3,0.1

Type RM Length L Ch R = 1 ,420.4   ,191.5,191.8,189.1
XS GIS Cut Line= 4
     2266688.458      380359.476     2266795.229      380410.257
     2267059.552      380165.465     2267036.114       380080.83
#Sta/Elev= 30
       0  508.55     7.9  512.15   15.32516.9704    23.6   522.3    27.6  523.49
   62.08522.7628      67  520.32    86.7  504.52    94.6  500.64   118.2   499.6
   153.9  502.09   185.5  500.31   197.4  498.78   209.3  492.74  218.63492.3528
   225.1  492.27     233  491.36   244.9  491.47   246.7492.4555   264.7  505.82
   268.7  507.66   351.8  510.69   383.5  509.75   419.1   512.6   446.8  510.59
     487   514.8   502.4  521.55   510.4  523.46  530.99523.3047   566.3  524.93
#Mann= 8 ,-1 , 0
       0     .12       0   15.32    .016       0   62.08     .12       0
  218.63     .04       0   225.1    .045       0   246.7     .12       0
     487    .016       0  530.99     .12       0
Bank Sta=225.1,246.7
XS Rating Curve= 0 ,0
Exp/Cntr=0.3,0.1

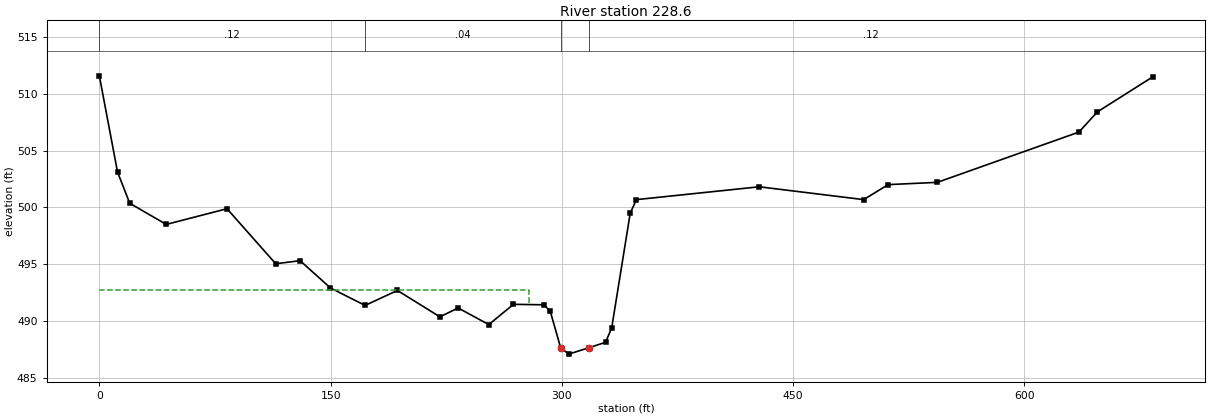
Type RM Length L Ch R = 1 ,228.6   ,229.4,228.6,229.1
XS GIS Cut Line= 4
     2266747.052      380407.653     2266948.874      380523.538
     2267148.093      380339.945     2267088.197      380170.674
#Sta/Elev= 30
       0  511.57    11.8  503.11    19.7  500.36    43.4   498.5    82.8  499.88
   114.4  495.04   130.2  495.31   149.9  492.91  172.34491.3736   193.3  492.69
   220.9  490.37   232.7  491.15   252.6  489.69   268.6  491.47   288.5  491.43
   292.5  490.84  299.13487.6721   304.4  487.09   317.6 487.657   328.3  488.13
   332.3   489.4   344.3  499.48   348.3  500.68     428  501.81   495.7  500.68
   511.6     502   543.5   502.2   635.3  506.62   647.3   508.4   683.2  511.48
#Mann= 4 ,-1 , 0
       0     .12       0  172.34     .04       0  299.13    .045       0
   317.6     .12       0
#XS Ineff= 2 , 0
          278.84   492.7
Permanent Ineff=
       F       F
Bank Sta=299.13,317.6
XS Rating Curve= 0 ,0
Exp/Cntr=0.3,0.1
LCMann Table=0

Chan Stop Cuts=-1
Use User Specified Reach Order=0
Composite Channel Slope=5